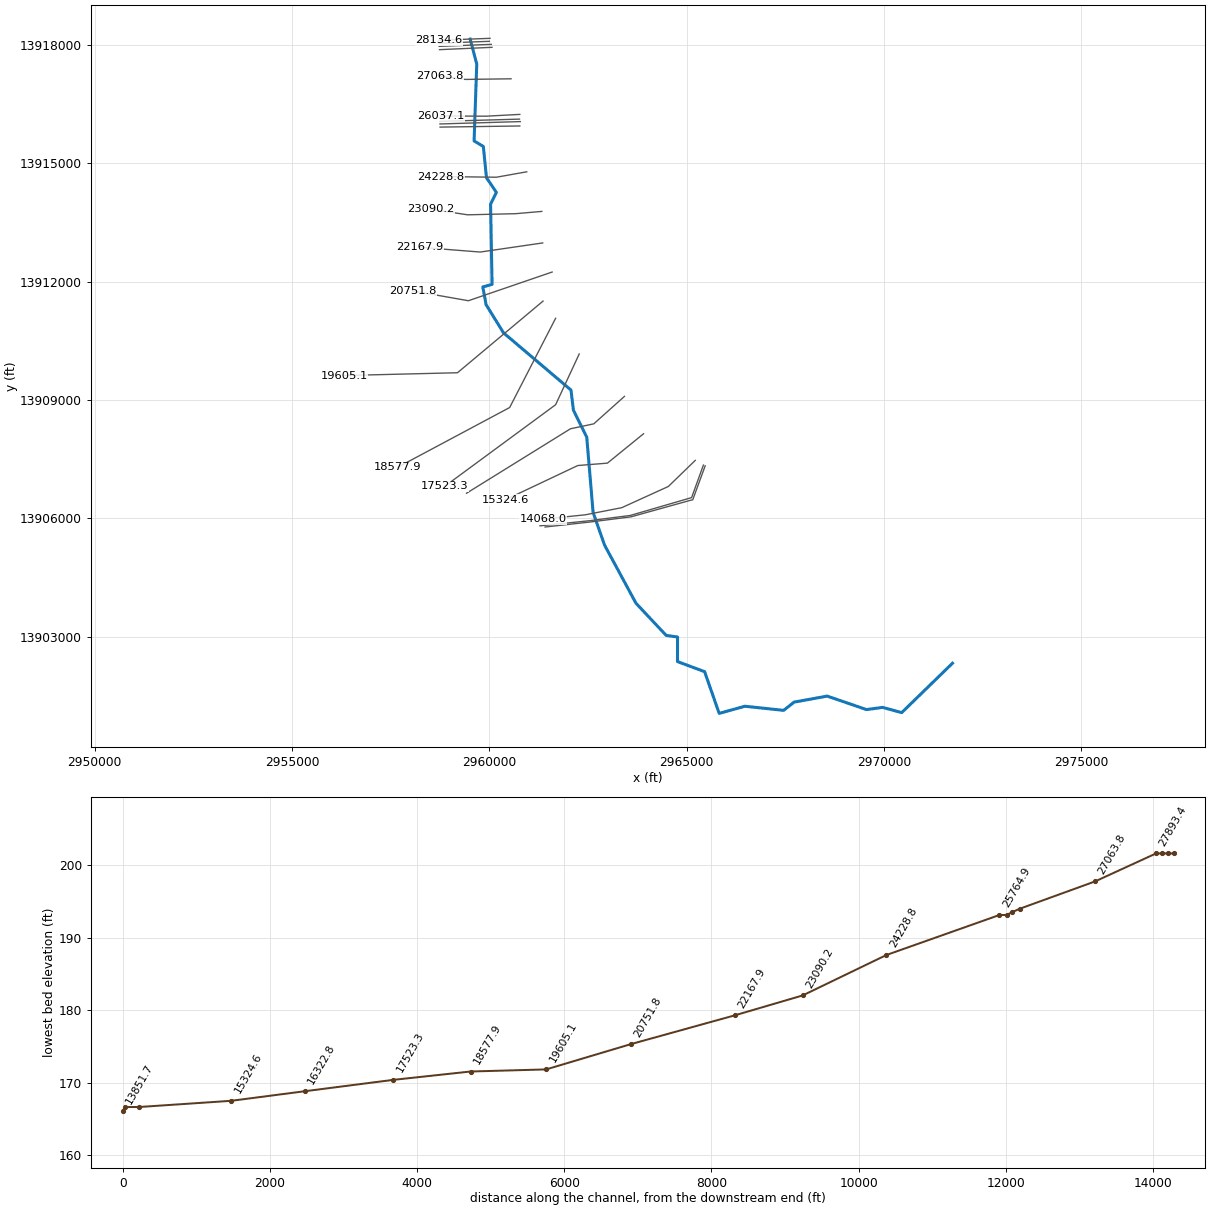
--- K172-00-00.prj (project) ---

Proj Title=K172-00-00
Current Plan=p06
Default Exp/Contr=0.3,0.1
English Units
Geom File=g01
Flow File=f05
Flow File=f06
Plan File=p06
Plan File=p01
Y Axis Title=Elevation
X Axis Title(PF)=Main Channel Distance
X Axis Title(XS)=Station
BEGIN DESCRIPTION:
Cypress Creek Watershed
Cypress Creek Trib 44.5
HCFCD Unit K172-00-00 and Unit K185-00-00 (K185-00-00 from cross section 4473.1 to 6901.1, K172-00-00 from cross section 8204.1 to 28134.6)
Flood Hazard Model
10, 2, 1, 0.2%
Filename K172-00-00
Prepared by:  Halff Associates, Inc.  DATE:  April 16, 2004
Reviewed by:  _________  DATE:  __________________
STATUS (Final Draft)
TROPICAL STORM ALLISON RECOVERY PROJECT
END DESCRIPTION:
DSS Export Rating Curves= 0
DSS Export Rating Curve Sorted= 0
DSS Export Volume Flow Curves= 0
DXF OffsetX= 0
DXF OffsetY= 0
DXF ScaleX= 1
DXF ScaleY= 10

--- K172-00-00.p06 (plan) ---

Plan Title=Effective FW 2013
Program Version=3.13
Short Identifier=Eff FW 2013
Geom File=g01
Flow File=f05
Subcritical Flow
K Sum by GR= 0
Std Step Tol= 0.01
Critical Tol= 0.01
Num of Std Step Trials= 20
Max Error Tol= 0.3
Flow Tol Ratio= 0.001
Split Flow NTrial= 30
Split Flow Tol= 0.02
Split Flow Ratio= 0.02
Log Output Level= 0
Friction Slope Method= 1
Unsteady Friction Slope Method= 2
Unsteady Bridges Friction Slope Method= 1
Parabolic Critical Depth
Global Vel Dist= 0 , 0 , 0
Global Log Level= 0
CheckData=True
Encroach Param=-1 ,0,0, 3
Encroach River=K172-00-00
Encroach Reach=K172-00-00_0045
Encroach Node=28134.6
       1    4970    5040       1    4970    5040
Encroach Node=28058.8
       1    4900    5100       1    4900    5100
Encroach Node=28009.9
       0                       1    4900    5100
Encroach Node=27978.0
       1    4900    5100       1    4900    5100
Encroach Node=27893.4
       1    4950    5020       1    4950    5020
Encroach Node=27063.8
       1  4993.2  5006.5       1    4960    5040
Encroach Node=26037.1
       1    4975  5011.4       1    4975    5055
Encroach Node=25929.0
       1 4992.16 5013.53       1    4980    5090
Encroach Node=25890.4
       0                       1    4980    5090
Encroach Node=25861.9
       1  4991.6  5011.6       1    4980    5090
Encroach Node=25764.9
       1    4940    5040       1    4940    5040
Encroach Node=24228.8
       1    4940    5020       1    4930    5060
Encroach Node=23090.2
       1    4940    5070       1    4940    5070
Encroach Node=22167.9
       1    4900    5150       1    4900    5150
Encroach Node=20751.8
       1    4825    5230       1    4900    5230
Encroach Node=19605.1
       1    4825    5100       1    4800    5850
Encroach Node=18577.9
       1    4825    5100       1    4800    5900
Encroach Node=17523.3
       1    4825    5100       1    4800    5500
Encroach Node=16322.8
       1    4930    5250       1    4930    5530
Encroach Node=15324.6
       1    4950    5300       1    4950    5560
Encroach Node=14068.0
       1    4470    5300       1    4200    5350
Encroach Node=13886.4
       1    4450    5300       1    4050    5350
Encroach Node=13874.0
       0                       1    4050    5350
Encroach Node=13851.7
       1    4450    5300       1    4050    5350
Encroach Node=13839.0
       1    4450    5307       1    4000    5400
Encroach Node=13828.3
       0                       1    4000    5400
Encroach Node=13818.0
       1    4450    5310       1    4000    5400
Encroach Node=13669.8
       1    4447    5310       1    4000    5400
Encroach Node=12446.2
       1    4600    5370       1 4074.47    5700
Encroach Node=11308.6
       1 4672.47    5312       1    4000    5700
Encroach Node=10469.3
       1  4573.6    5312       1    4000    5700
Encroach Node=9198.0
       1    4581    5512       1    4300    6000
Encroach Node=8204.1
       1    4742    5500       1    4500    6000
Encroach Node=6901.1
       1    4770  5489.4       1 4371.68 5982.12
Encroach Node=5443.3
       1    4750    5700       1    4650    6000
Encroach Node=5340.5
       1    4750    5700       1    4650    6000
Encroach Node=5308.0
       0                       1    4650    6000
Encroach Node=5285.7
       1    4750    5700       1    4650    6000
Encroach Node=5175.2
       1    4700    5700       1    4650    6000
Encroach Node=4473.1
       1  4985.7    5875       1    4800    6000
BEGIN DESCRIPTION:
FEMA Effective Floodway October 2013
END DESCRIPTION:
Computation Interval=1HOUR
Output Interval=1HOUR
Run HTab= 0
Run UNet= 0
Run PostProcess= 0
UNET Theta= 1
UNET Theta Warmup= 1
UNET ZTol= 0.02
UNET ZSATol= 0.1
UNET MxIter= 20
UNET MaxInSteps= 20
UNET DtIC= 0
UNET DtMin= 0
UNET MaxCRTS= 20
UNET WFStab= 2
UNET SFStab= 1
UNET WFX= 1
UNET SFX= 1
UNET DSS MLevel= 4
UNET DZMax Abort= 100
UNET Convert EG Bridges=-1
UNET Use Existing IB Tables=-1
UNET Froude Reduction=False
UNET Froude Limit= 1
UNET Froude Power= 10
Instantaneous Interval=1HOUR
Write IC File= 0
IC Time=0,,
Echo Input=False
Echo Output=False
Write Detailed= 0
Detailed Automatic Start=False, 10

--- K172-00-00.p01 (plan) ---

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Plan Title=Effective MP 2013
Short Identifier=Eff MP 2013
Geom File=g01
Flow File=f06
Encroach Param=-1 ,0,0, 2
FEMA Effective MP October 2013

--- K172-00-00.f05 (steady flow) ---

Flow Title=Effective FW 2013
Program Version=3.13
Number of Profiles= 2
Profile Names=1PCT_100yr,1PCTFloodway_10
River Rch & RM=K172-00-00,K172-00-00_0045       ,28134.6
     226     226
River Rch & RM=K172-00-00,K172-00-00_0045       ,26037.1
     242     242
River Rch & RM=K172-00-00,K172-00-00_0045       ,24228.8
     318     318
River Rch & RM=K172-00-00,K172-00-00_0045       ,23090.2
     332     332
River Rch & RM=K172-00-00,K172-00-00_0045       ,22167.9
     350     350
River Rch & RM=K172-00-00,K172-00-00_0045       ,20751.8
     357     357
River Rch & RM=K172-00-00,K172-00-00_0045       ,19605.1
     446     446
River Rch & RM=K172-00-00,K172-00-00_0045       ,18577.9
     706     706
River Rch & RM=K172-00-00,K172-00-00_0045       ,17523.3
     726     726
River Rch & RM=K172-00-00,K172-00-00_0045       ,16322.8
     731     731
River Rch & RM=K172-00-00,K172-00-00_0045       ,15324.6
     733     733
River Rch & RM=K172-00-00,K172-00-00_0045       ,14068.0
     776     776
River Rch & RM=K172-00-00,K172-00-00_0045       ,12446.2
     788     788
River Rch & RM=K172-00-00,K172-00-00_0045       ,10469.3
     801     801
River Rch & RM=K172-00-00,K172-00-00_0045       ,9198.0
     985     985
River Rch & RM=K172-00-00,K172-00-00_0045       ,8204.1
    1064    1064
River Rch & RM=K172-00-00,K172-00-00_0045       ,6901.1
    1065    1065
River Rch & RM=K172-00-00,K172-00-00_0045       ,5340.5
    1085    1085
River Rch & RM=K172-00-00,K172-00-00_0045       ,4473.1
    1198    1198
Boundary for River Rch & Prof#=K172-00-00,K172-00-00_0045       , 1
Up Type= 0
Dn Type= 3
Dn Slope=0.0009
Boundary for River Rch & Prof#=K172-00-00,K172-00-00_0045       , 2
Up Type= 0
Dn Type= 3
Dn Slope=0.0009
DSS Import GetInterval= 0
DSS Import GetPeak= 0
DSS Import FillOption= 0

--- K172-00-00.f06 (steady flow) ---

Flow Title=Effective MP 2013
Program Version=3.13
Number of Profiles= 4
Profile Names=10PCT_10yr,2PCT_50yr,1PCT_100yr,0.2PCT_500yr
River Rch & RM=K172-00-00,K172-00-00_0045       ,28134.6
      78     167     226     429
River Rch & RM=K172-00-00,K172-00-00_0045       ,26037.1
      83     178     242     459
River Rch & RM=K172-00-00,K172-00-00_0045       ,24228.8
     110     235     318     605
River Rch & RM=K172-00-00,K172-00-00_0045       ,23090.2
     114     245     332     631
River Rch & RM=K172-00-00,K172-00-00_0045       ,22167.9
     121     259     350     666
River Rch & RM=K172-00-00,K172-00-00_0045       ,20751.8
     123     264     357     679
River Rch & RM=K172-00-00,K172-00-00_0045       ,19605.1
     154     329     446     847
River Rch & RM=K172-00-00,K172-00-00_0045       ,18577.9
     243     521     706    1342
River Rch & RM=K172-00-00,K172-00-00_0045       ,17523.3
     250     536     726    1381
River Rch & RM=K172-00-00,K172-00-00_0045       ,16322.8
     252     540     731    1390
River Rch & RM=K172-00-00,K172-00-00_0045       ,15324.6
     253     541     733    1394
River Rch & RM=K172-00-00,K172-00-00_0045       ,14068.0
     267     573     776    1475
River Rch & RM=K172-00-00,K172-00-00_0045       ,12446.2
     271     582     788    1497
River Rch & RM=K172-00-00,K172-00-00_0045       ,10469.3
     276     592     801    1523
River Rch & RM=K172-00-00,K172-00-00_0045       ,9198.0
     339     727     985    1872
River Rch & RM=K172-00-00,K172-00-00_0045       ,8204.1
     366     785    1064    2022
River Rch & RM=K172-00-00,K172-00-00_0045       ,6901.1
     367     787    1065    2025
River Rch & RM=K172-00-00,K172-00-00_0045       ,5340.5
     374     801    1085    2063
River Rch & RM=K172-00-00,K172-00-00_0045       ,4473.1
     413     885    1198    2278
Boundary for River Rch & Prof#=K172-00-00,K172-00-00_0045       , 1
Up Type= 0
Dn Type= 3
Dn Slope=0.0009
Boundary for River Rch & Prof#=K172-00-00,K172-00-00_0045       , 2
Up Type= 0
Dn Type= 3
Dn Slope=0.0009
Boundary for River Rch & Prof#=K172-00-00,K172-00-00_0045       , 3
Up Type= 0
Dn Type= 3
Dn Slope=0.0009
Boundary for River Rch & Prof#=K172-00-00,K172-00-00_0045       , 4
Up Type= 0
Dn Type= 3
Dn Slope=0.0009
DSS Import GetInterval= 0
DSS Import GetPeak= 0
DSS Import FillOption= 0

--- K172-00-00.g01 (geometry) ---

Geom Title=K172-00-00 2013
Program Version=3.13

River Reach=K172-00-00      ,K172-00-00_0045
Reach XY= 30
 2959515.4189227 13918147.837739       2959682.5     13917515.87
      2959615.23     13915567.41      2959849.02     13915428.28
      2959929.13     13914634.13      2960179.76     13914263.71
      2960032.55     13913962.78      2960070.91     13911931.71
      2959835.67      13911866.6        2959919.     13911418.69
       2960359.8     13910704.62      2962070.08      13909254.2
      2962132.51     13908743.65      2962469.76     13908059.82
      2962630.94     13906151.79      2962920.69     13905325.41
      2963717.25     13903852.46      2964483.07     13903036.33
      2964770.95     13902996.27      2964769.09     13902373.92
      2965456.65     13902117.72      2965825.59     13901061.22
      2966476.81     13901241.96      2967458.78     13901137.62
      2967723.37     13901346.31      2968562.79      13901499.1
      2969559.66     13901157.18      2969966.79     13901213.08
      2970450.98     13901080.26 2971737.5431963 13902331.766405

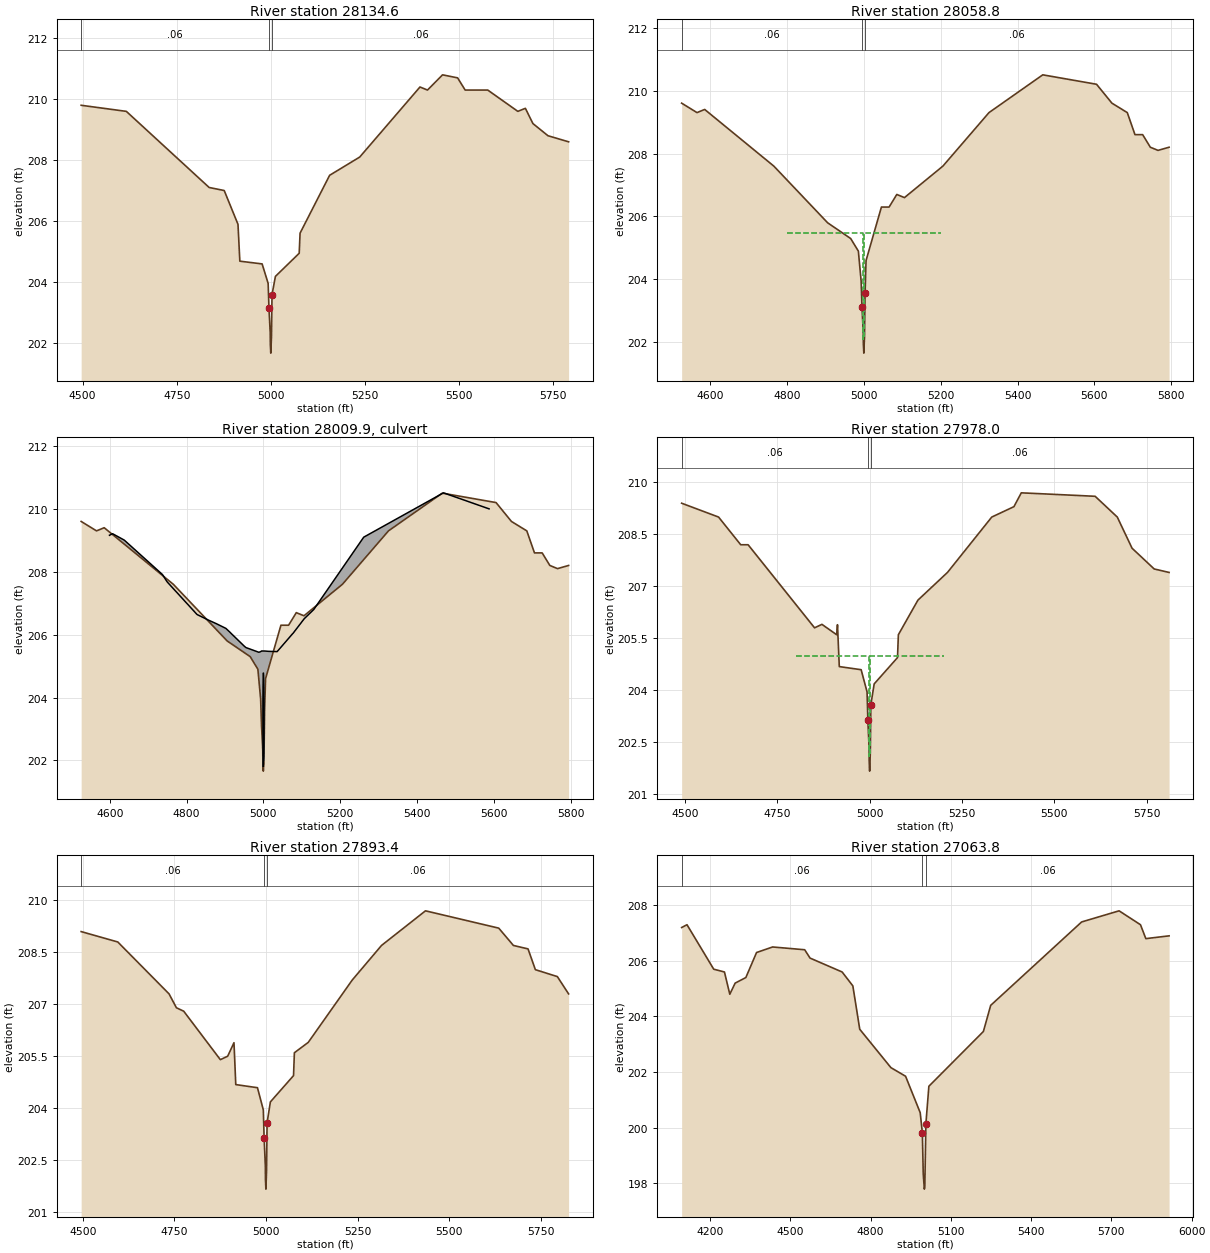
Type RM Length L Ch R = 1 ,28134.6 ,75.3,75.8,75
BEGIN DESCRIPTION:
K161-00-00-S5_UNNAMED RD - U/S - XS4
Limits of Study
END DESCRIPTION:
XS GIS Cut Line= 2
      2960018.92      13918166.7      2958725.08     13918118.01
#Sta/Elev= 30
  4496.1   209.8  4616.1   209.6  4836.1   207.1  4876.1     207  4912.7  205.89
  4917.6  204.68  4976.8  204.59  4992.8  203.95    4995  203.13  4998.3  202.33
  4998.6  201.95  4999.8  201.66  5001.6  202.19  5003.1  203.58  5012.1  204.18
  5075.3  204.94  5077.6   205.6  5156.1   207.5  5236.1   208.1  5396.1   210.4
  5416.1   210.3  5456.1   210.8  5496.1   210.7  5516.1   210.3  5576.1   210.3
  5656.1   209.6  5676.1   209.7  5696.1   209.2  5736.1   208.8  5790.9   208.6
#Mann= 3 , 0 , 0
  4496.1     .06       0    4995     .05       0  5003.1     .06       0
Bank Sta=4995,5003.1
Exp/Cntr=0.5,0.3

Type RM Length L Ch R = 1 ,28058.8 ,79.1,80.8,79.3
BEGIN DESCRIPTION:
K161-00-00-S5_UNNAMED RD - U/S - XS3
END DESCRIPTION:
XS GIS Cut Line= 2
      2960002.89       13918091.      2958734.99     13918043.62
#Sta/Elev= 30
  4525.6   209.6  4565.6   209.3  4585.6   209.4  4765.6   207.6  4905.6   205.8
  4965.6   205.3  4985.6   204.9  4992.8  203.95    4995  203.13  4998.3  202.33
  4998.6  201.95  4999.8  201.66  5001.6  202.19  5003.1  203.58  5005.6   204.6
  5045.6   206.3  5065.6   206.3  5085.6   206.7  5105.6   206.6  5205.6   207.6
  5325.6   209.3  5465.6   210.5  5605.6   210.2  5645.6   209.6  5685.6   209.3
  5705.6   208.6  5725.6   208.6  5745.6   208.2  5765.6   208.1  5794.4   208.2
#Mann= 3 , 0 , 0
  4525.6     .06       0    4995     .05       0  5003.1     .06       0
#XS Ineff= 2 ,-1
    4800  4998.5  205.48 5001.49    5200  205.48
Permanent Ineff=
       T       F
Bank Sta=4995,5003.1
Exp/Cntr=0.5,0.3

Type RM Length L Ch R = 2 ,28009.9 ,,,
BEGIN DESCRIPTION:
UNNAMED ROAD 2000' US ARRIOLA
Structure ID: K172-00-00-S5
END DESCRIPTION:
Bridge Culvert--1,0,-1,-1, 0
Deck Dist Width WeirC Skew NumUp NumDn MinLoCord MaxHiCord MaxSubmerge Is_Ogee
10,60,3,0, 34, 35, , , 0.95, 0, ,,,
  4599.3  4607.3  4637.3  4639.3  4737.3  4749.3  4827.3  4857.3  4877.3  4902.2
  4912.7  4917.6  4949.7  4954.4  4976.8  4988.1  4992.8    4995  4995.8  4998.3
  4998.6  4999.8  5001.6  5003.1  5012.1  5035.6  5041.4  5075.3  5077.6  5106.5
  5131.1  5261.1  5468.7  5587.4
  209.16  209.21  209.01  208.99  207.91  207.68  206.64  206.46  206.35   206.2
  206.08  206.02  205.64  205.59  205.49  205.44  205.46  205.48  205.48  205.48
  205.48  205.48  205.48  205.48  205.47  205.46  205.54  206.02  206.05  206.51
   206.8   209.1  210.51     210
                                                                                
                                                                                
                                                                                
                                
  4590.6  4599.3  4607.3  4637.3  4639.3  4737.3  4749.3  4827.3  4857.3  4877.3
  4902.2  4912.7  4917.6  4949.7  4954.4  4976.8  4988.1  4992.8    4995  4995.8
  4998.3  4998.6  4999.8  5001.6  5003.1  5012.1  5035.6  5041.4  5075.3  5077.6
  5106.5  5131.1  5261.1  5468.7  5587.4
     209  209.16  209.21  209.01  208.99  207.91  207.68  206.64  206.46  206.35
   206.2  206.08  206.02  205.64  205.59  205.49  205.44  205.46  205.48  205.48
  205.48  205.48  205.48  205.48  205.48  205.47  205.46  205.54  206.02  206.05
  206.51   206.8   209.1  210.51  209.69
                                                                                
                                                                                
                                                                                
                                        
BR Coef= 1 , 0 , 0 ,1.25, 0 ,,,0.8,0,2,0,
WSPro=,,,, 1 ,,,, 0 ,,,, 0 ,,,,-1 ,-1 ,-1 , 0 , 0 , 0 , 0 , 0
Culvert=1,3,,60,0.015,0.2,1,1,3,201.79,5000,201.25,5000,Culvert #1  , 0 ,10
Culvert Bottom n=0.015
BC Design=,, 0 ,, 0 ,,,,,,
BC HTab HWMax=226.02

Type RM Length L Ch R = 1 ,27978.0 ,78,84.6,79.9
BEGIN DESCRIPTION:
K161-00-00-S5_UNNAMED RD - D/S - XS2
END DESCRIPTION:
XS GIS Cut Line= 2
      2960050.06      13918014.3      2958730.75     13917963.16
#Sta/Elev= 30
  4490.6   209.4  4590.6     209  4650.6   208.2  4670.6   208.2  4850.6   205.8
  4870.6   205.9  4910.6   205.6  4912.7  205.89  4917.6  204.68  4976.8  204.59
  4992.8  203.95    4995  203.13  4998.3  202.33  4998.6  201.95  4999.8  201.66
  5001.6  202.19  5003.1  203.58  5012.1  204.18  5075.3  204.94  5077.6   205.6
  5130.6   206.6  5210.6   207.4  5330.6     209  5390.6   209.3  5410.6   209.7
  5610.6   209.6  5670.6     209  5710.6   208.1  5770.6   207.5  5810.9   207.4
#Mann= 3 , 0 , 0
  4490.6     .06       0    4995     .05       0  5003.1     .06       0
#XS Ineff= 2 ,-1
    4800  4998.5     205 5001.49    5200     205
Permanent Ineff=
       T       F
Bank Sta=4995,5003.1
Exp/Cntr=0.5,0.3

Type RM Length L Ch R = 1 ,27893.4 ,799.5,829.6,785.6
BEGIN DESCRIPTION:
K161-00-00-S5_UNNAMED RD - D/S - XS1
END DESCRIPTION:
XS GIS Cut Line= 2
      2960068.61      13917939.1      2958739.28     13917879.56
#Sta/Elev= 30
  4495.5   209.1  4595.5   208.8  4735.5   207.3  4755.5   206.9  4775.5   206.8
  4875.5   205.4  4895.5   205.5  4912.7  205.89  4917.6  204.68  4976.8  204.59
  4992.8  203.95    4995  203.13  4998.3  202.33  4998.6  201.95  4999.8  201.66
  5001.6  202.19  5003.1  203.58  5012.1  204.18  5075.3  204.94  5077.6   205.6
  5115.5   205.9  5235.5   207.7  5315.5   208.7  5435.5   209.7  5635.5   209.2
  5675.5   208.7  5715.5   208.6  5735.5     208  5795.5   207.8  5826.2   207.3
#Mann= 3 , 0 , 0
  4495.5     .06       0    4995     .05       0  5003.1     .06       0
Bank Sta=4995,5003.1
Exp/Cntr=0.3,0.1

Type RM Length L Ch R = 1 ,27063.8 ,939.2,1026.7,934.4
BEGIN DESCRIPTION:
Cross Section K161-00-00-X17
END DESCRIPTION:
XS GIS Cut Line= 3
      2960551.78     13917141.58      2959396.59     13917125.42
      2958734.99     13917209.34
#Sta/Elev= 30
  4093.4   207.2  4113.4   207.3  4213.4   205.7  4253.4   205.6  4273.4   204.8
  4293.4   205.2  4333.4   205.4  4373.4   206.3  4433.4   206.5  4553.4   206.4
  4573.4   206.1  4693.4   205.6  4733.4   205.1  4759.2  203.54  4875.7  202.16
  4930.5  201.85  4985.2  200.54  4993.2  199.82  4996.6  198.33  5000.7  197.79
  5002.4  197.87  5006.5  200.15  5017.6  201.49  5221.4  203.46  5248.7   204.4
  5588.7   207.4  5728.7   207.8  5808.7   207.3  5828.7   206.8  5915.6   206.9
#Mann= 3 , 0 , 0
  4093.4     .06       0  4993.2     .05       0  5006.5     .06       0
Bank Sta=4993.2,5006.5
Exp/Cntr=0.3,0.1

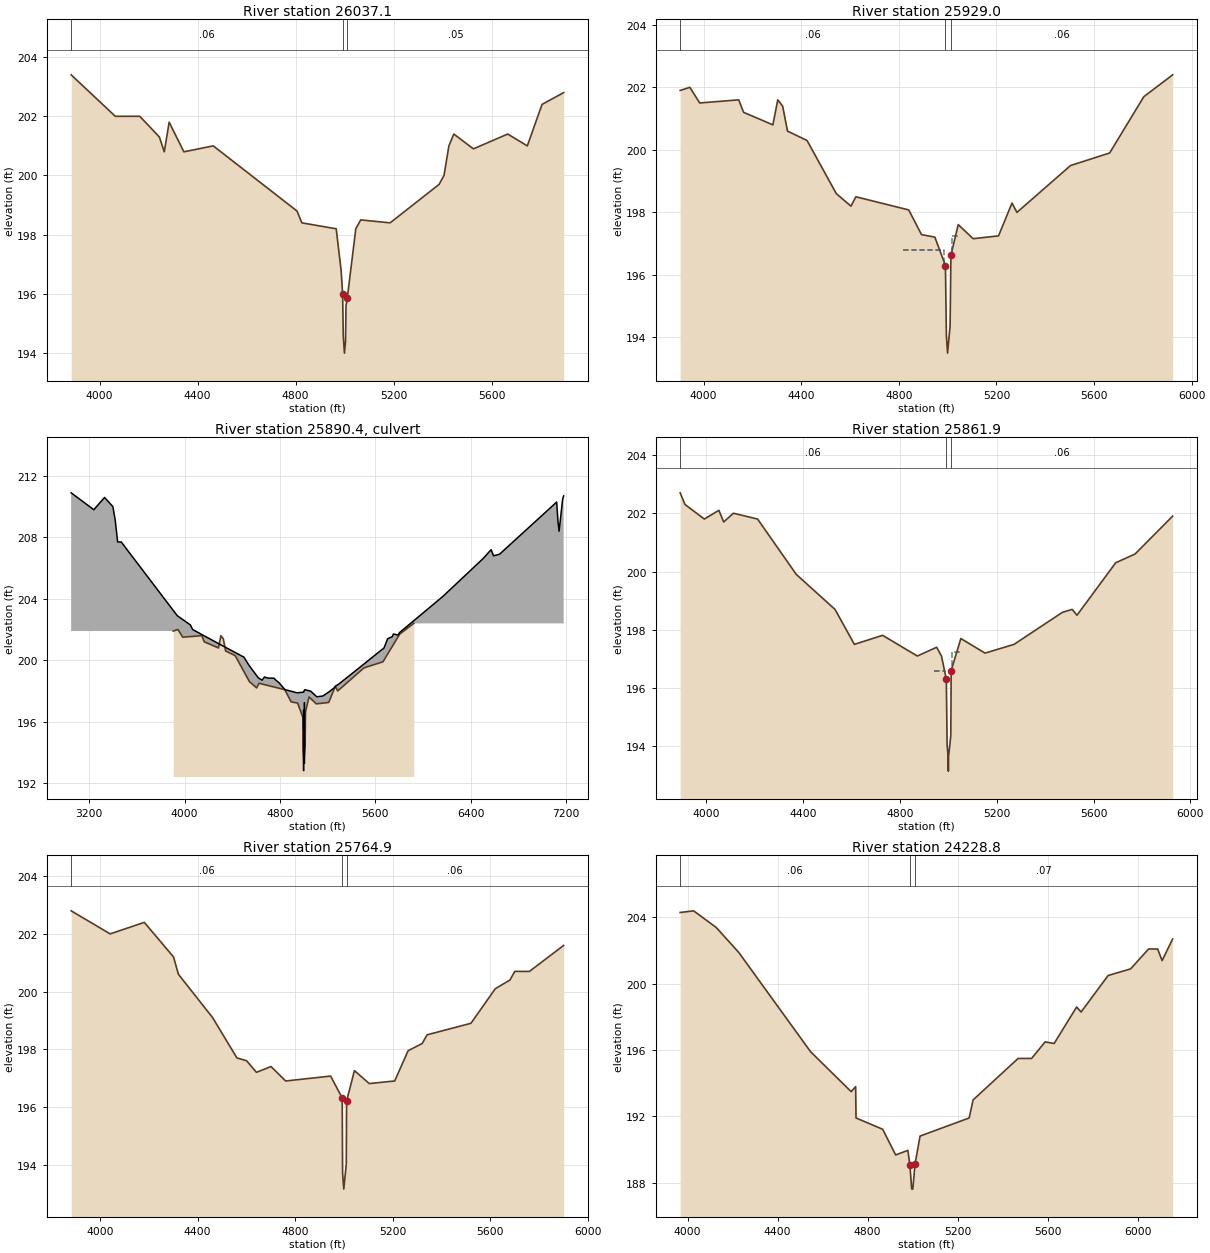
Type RM Length L Ch R = 1 ,26037.1 ,100.4,108.1,114.9
BEGIN DESCRIPTION:
K161-00-00-SO4_PRIVATE RD - U/S - XS4
END DESCRIPTION:
XS GIS Cut Line= 3
      2960773.45     13916239.32      2959912.94     13916193.73
      2958764.64     13916199.43
#Sta/Elev= 30
  3884.3   203.4  4064.3     202  4164.3     202  4244.3   201.3  4264.3   200.8
  4284.3   201.8  4344.3   200.8  4464.3     201    4806   198.8    4826   198.4
    4966   198.2    4986   196.8 4992.16  196.01  4994.9  194.56  4999.7     194
    5004  194.38    5006   195.6  5011.4  195.87    5046   198.2    5066   198.5
    5186   198.4    5386   199.7    5406     200    5426     201    5446   201.4
    5526   200.9    5666   201.4    5746     201    5806   202.4  5894.3   202.8
#Mann= 3 , 0 , 0
  3884.3     .06       0 4992.16     .06       0  5011.4     .05       0
Bank Sta=4992.16,5011.4
Exp/Cntr=0.5,0.3

Type RM Length L Ch R = 1 ,25929.0 ,64.4,67.1,65.3
BEGIN DESCRIPTION:
K161-00-00-SO4_PRIVATE RD - U/S - XS3
END DESCRIPTION:
XS GIS Cut Line= 2
       2960764.9     13916119.65      2958747.55     13916062.66
#Sta/Elev= 30
  3903.9   201.9  3943.9     202  3983.9   201.5  4143.9   201.6  4163.9   201.2
  4283.9   200.8  4303.9   201.6  4323.9   201.4  4343.9   200.6  4423.9   200.3
  4543.9   198.6  4603.9   198.2  4623.9   198.5  4840.6  198.08  4892.9  197.29
  4947.7  197.21    4991   196.3  4994.9  194.06  4999.7   193.5  5010.1  194.37
 5013.53  196.63  5043.5  197.61  5104.4  197.16  5208.6  197.25  5263.8   198.3
  5283.9     198  5503.9   199.5  5663.9   199.9  5803.9   201.7  5922.1   202.4
#Mann= 3 , 0 , 0
  3903.9     .06       0    4991     .06       0 5013.53     .06       0
#XS Ineff= 2 ,-1
  5016.8 5049.26  197.25 4819.08  4985.5   196.8
Permanent Ineff=
       F       F
Bank Sta=4991,5013.53
Exp/Cntr=0.5,0.3

Type RM Length L Ch R = 2 ,25890.4 ,,,
BEGIN DESCRIPTION:
PRIVATE RD 1100' US ARRIOLA
Structure ID: K172-00-00-S04
END DESCRIPTION:
Bridge Culvert--1,0,-1,-1, 0
Deck Dist Width WeirC Skew NumUp NumDn MinLoCord MaxHiCord MaxSubmerge Is_Ogee
15,20,3,0, 69, 69, , , 0.95, 0, ,,,
  3047.9  3237.9  3327.9  3397.9  3417.9  3437.9  3467.9  3937.9  4047.9  4067.3
  4077.9  4097.9  4109.6  4137.3  4299.6  4359.6  4497.3  4539.6  4617.3  4649.6
  4669.6  4697.3  4749.6  4761.2  4790.8  4792.1  4840.6  4840.9  4942.3  4996.9
  4999.5  4999.6  4999.7  5000.2  5000.4    5004  5007.6  5010.1  5043.5  5056.8
  5104.4  5108.5  5156.9  5158.8  5208.6  5212.6  5261.4  5263.8  5286.5  5426.5
  5636.5  5666.5    5671  5672.7  5702.7  5742.7    5751    5791  5802.7  6163.9
    6501    6571    6591    6641    7121    7131    7141    7171  7179.4
   210.9   209.8   210.6     210   209.1   207.7   207.7   202.9   202.3     202
  201.95  201.87  201.82   201.7  201.02  200.77   200.2  199.67  198.86   198.7
  198.91  198.84  198.83  198.73  198.54  198.53  198.09  198.09  197.88  197.92
  197.96  197.96  197.96  197.97  197.97  198.03  198.08  198.08  198.01  197.99
  197.65  197.62  197.67  197.67  197.93  197.95  198.25  198.31  198.41  199.27
  200.58  200.76  200.79   200.8   201.4  201.54  201.71  201.64   201.8  204.14
   206.6   207.2   206.8   206.9   210.3   209.1   208.4   210.5   210.7
                                                                                
                                                                                
                                                                                
                                                                                
                                                                                
                                                                                
                                                                        
  3047.9  3237.9  3327.9  3397.9  3417.9  3437.9  3467.9  3937.9  4047.9  4067.3
  4077.9  4097.9  4109.6  4137.3  4299.6  4359.6  4497.3  4539.6  4617.3  4649.6
  4669.6  4697.3  4749.6  4761.2  4790.8  4792.1  4840.6  4840.9  4942.3  4996.9
  4999.5  4999.6  4999.7  5000.2  5000.4    5004  5007.6  5010.1  5043.5  5056.8
  5104.4  5108.5  5156.9  5158.8  5208.6  5212.6  5261.4  5263.8  5286.5  5426.5
  5636.5  5666.5    5671  5672.7  5702.7  5742.7    5751    5791  5802.7  6163.9
    6501    6571    6591    6641    7121    7131    7141    7171  7179.4
   210.9   209.8   210.6     210   209.1   207.7   207.7   202.9   202.3     202
  201.95  201.87  201.82   201.7  201.02  200.77   200.2  199.67  198.86   198.7
  198.91  198.84  198.83  198.73  198.54  198.53  198.09  198.09  197.88  197.92
  197.96  197.96  197.96  197.97  197.97  198.03  198.08  198.08  198.01  197.99
  197.65  197.62  197.67  197.67  197.93  197.95  198.25  198.31  198.41  199.27
  200.58  200.76  200.79   200.8   201.4  201.54  201.71  201.64   201.8  204.14
   206.6   207.2   206.8   206.9   210.3   209.1   208.4   210.5   210.7
                                                                                
                                                                                
                                                                                
                                                                                
                                                                                
                                                                                
                                                                        
BR Coef= 1 , 0 , 0 ,1.25, 0 ,,,0.8,-1,2,0,
WSPro=,,,, 1 ,,,, 0 ,,,, 0 ,,,,-1 ,-1 ,-1 , 0 , 0 , 0 , 0 , 0
Culvert=1,4,,20,0.015,0.2,1,1,3,192.78,4997.5,192.81,4997.5,Culvert #1  , 0 ,15
Culvert Bottom n=0.015
Culvert=1,4,,20,0.015,0.2,1,1,3,193.26,5004.8,192.93,5004.8,Culvert #2  , 0 ,15
Culvert Bottom n=0.015
BC Design=,, 0 ,, 0 ,,,,,,
BC HTab HWMax=210.93

Type RM Length L Ch R = 1 ,25861.9 ,96.7,97,90.6
BEGIN DESCRIPTION:
K161-00-00-SO4_PRIVATE RD - D/S - XS2
END DESCRIPTION:
XS GIS Cut Line= 2
      2960784.85     13916056.96       2958750.4     13915997.12
#Sta/Elev= 30
  3891.6   202.7  3911.6   202.3  3991.6   201.8  4051.6   202.1  4071.6   201.7
  4111.6     202  4211.6   201.8  4371.6   199.9  4531.6   198.7  4611.6   197.5
 4728.23  197.81  4871.6   197.1  4951.6   197.4  4971.6   197.1  4991.6   196.3
  4994.9  194.06  4999.5  193.59 4999.96  193.15  5000.4  193.61  5010.1  194.37
  5011.6   196.6  5051.6   197.7  5151.6   197.2  5271.6   197.5  5471.6   198.6
  5511.6   198.7  5531.6   198.5  5691.6   200.3  5771.6   200.6  5926.9   201.9
#Mann= 3 , 0 , 0
  3891.6     .06       0  4991.6     .06       0  5011.6     .06       0
#XS Ineff= 2 ,-1
  5016.8  5050.2  197.25 4940.16  4985.5   196.6
Permanent Ineff=
       F       F
Bank Sta=4991.6,5011.6
Exp/Cntr=0.5,0.3

Type RM Length L Ch R = 1 ,25764.9 ,1384.5,1536.1,1387.2
BEGIN DESCRIPTION:
K161-00-00-SO4_PRIVATE RD - D/S - XS1
END DESCRIPTION:
XS GIS Cut Line= 2
      2960773.45     13915945.84      2958753.24     13915917.34
#Sta/Elev= 30
  3881.4   202.8  4041.4     202  4181.4   202.4  4301.4   201.2  4321.4   200.6
  4461.4   199.1  4561.4   197.7  4601.4   197.6  4641.4   197.2  4701.4   197.4
  4761.4   196.9 4945.73  197.07 4993.35  196.31 4993.35   196.2  4994.9  193.71
  4999.7  193.15  5010.1  194.02 5011.23   196.2  5043.5  197.26  5104.4  196.81
  5208.6   196.9  5263.8  197.95  5321.4   198.2  5341.4   198.5  5521.4   198.9
  5621.4   200.1  5681.4   200.4  5701.4   200.7  5761.4   200.7  5901.8   201.6
#Mann= 3 , 0 , 0
  3881.4     .06       0 4993.35     .06       0 5011.23     .06       0
Bank Sta=4993.35,5011.23
Exp/Cntr=0.3,0.1

Type RM Length L Ch R = 1 ,24228.8 ,946.9,1138.6,976.3
BEGIN DESCRIPTION:
Cross Section K161-00-00-X16
END DESCRIPTION:
XS GIS Cut Line= 3
      2960949.53     13914785.02       2960179.7     13914647.18
      2958773.01      13914664.7
#Sta/Elev= 30
  3966.9   204.3  4026.9   204.4  4126.9   203.4  4226.9   201.9  4546.9   195.9
  4726.9   193.5  4746.9   193.8  4748.6  191.91    4867  191.23  4924.8  189.68
    4979  189.96  4988.2  189.05  4995.9  187.63    5001  187.62  5010.4  189.11
  5033.3  190.82  5251.4  191.91    5269     193    5469   195.5    5529   195.5
    5589   196.5    5629   196.4    5729   198.6    5749   198.3    5869   200.5
    5969   200.9    6049   202.1    6089   202.1    6109   201.4  6155.8   202.7
#Mann= 3 , 0 , 0
  3966.9     .06       0  4988.2     .06       0  5010.4     .07       0
Bank Sta=4988.2,5010.4
Exp/Cntr=0.3,0.1

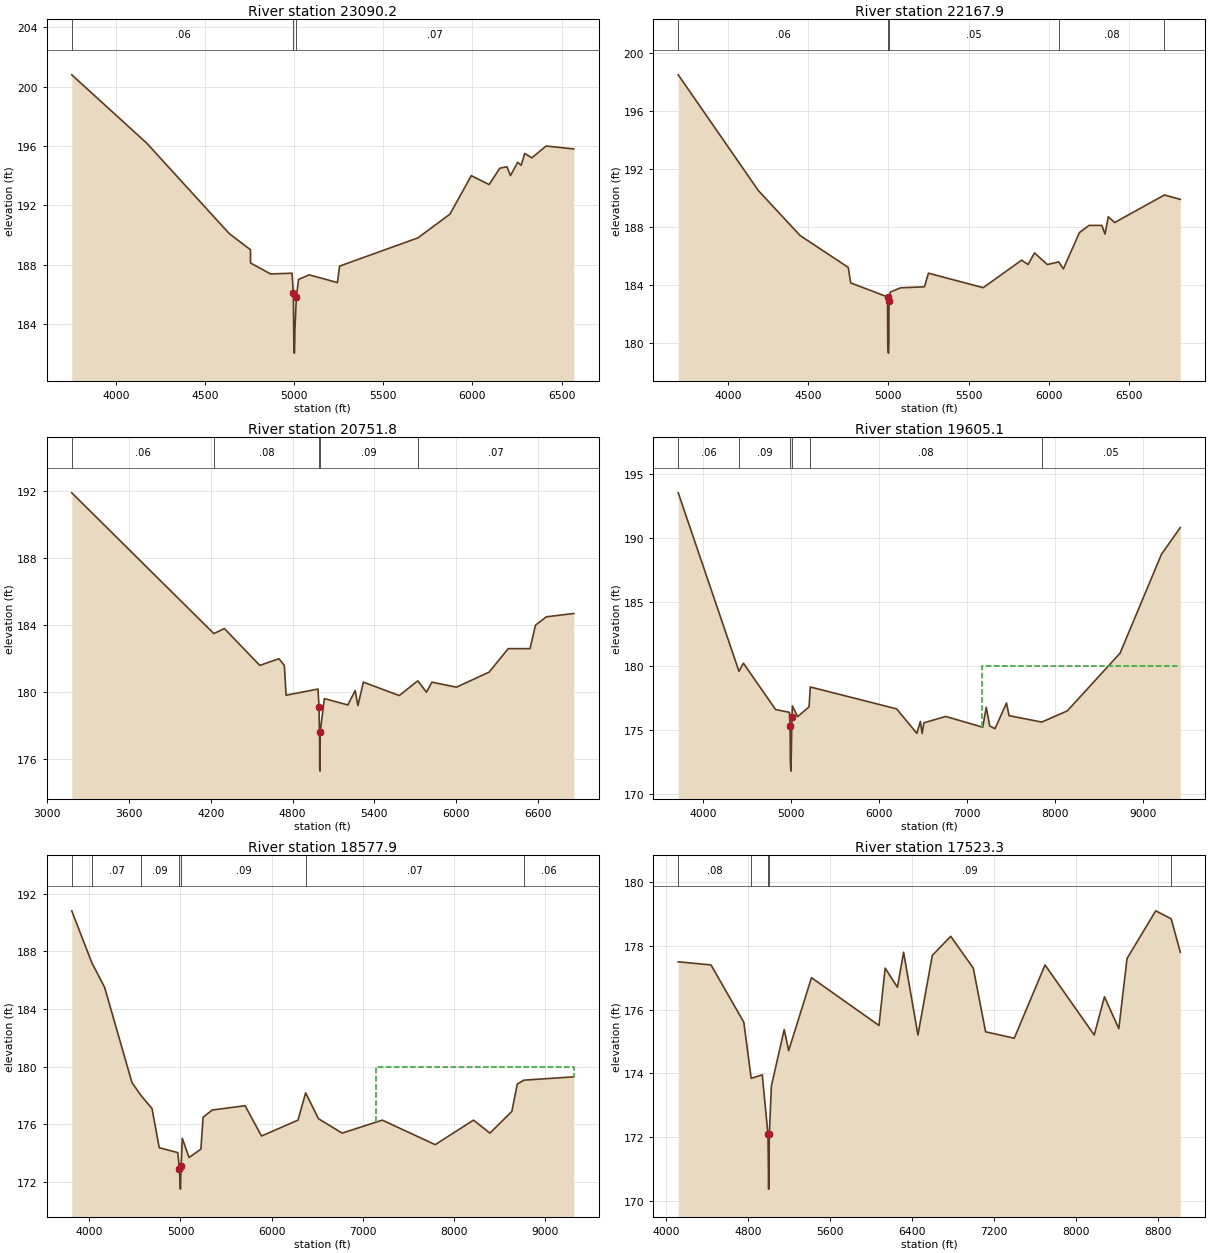
Type RM Length L Ch R = 1 ,23090.2 ,896.5,922.3,951
BEGIN DESCRIPTION:
Cross Section K161-00-00-X15
END DESCRIPTION:
XS GIS Cut Line= 4
      2961331.26     13913781.22      2960670.63     13913723.65
      2959452.08     13913694.64      2958527.17     13913834.99
#Sta/Elev= 30
  3751.5   200.8  4171.5   196.2  4634.6   190.1  4754.6     189  4754.8  188.11
  4866.7  187.37  4987.4  187.42  4994.8  186.11  4997.4  182.96  5000.5  182.03
    5003  182.78  5003.4  183.51  5011.8  185.83  5024.3     187  5083.7  187.31
  5242.1  186.79  5254.6   187.9  5693.5   189.8  5873.5   191.4  5993.5     194
  6093.5   193.4  6153.5   194.5  6193.5   194.6  6213.5     194  6253.5   194.9
  6273.5   194.7  6293.5   195.5  6333.5   195.2  6413.5     196    6569   195.8
#Mann= 3 ,-1 , 0
  3751.5     .06       0  4994.8     .07       0  5011.8     .07       0
Bank Sta=4994.8,5011.8
Exp/Cntr=0.3,0.1

Type RM Length L Ch R = 1 ,22167.9 ,1192.8,1416.1,1156.8
BEGIN DESCRIPTION:
Cross Section K161-00-00-X14
END DESCRIPTION:
XS GIS Cut Line= 3
      2961354.31     13912982.24      2959769.84     13912751.29
      2958245.37     13912871.48
#Sta/Elev= 30
  3690.2   198.5  4190.2   190.5  4450.2   187.4  4750.2   185.2  4765.5  184.13
  4995.1  183.16  4996.7  179.75  5000.8  179.28  5003.4  179.89  5003.5  181.21
  5004.6  182.91  5012.4   183.5  5076.6  183.79  5225.4  183.86  5250.2   184.8
  5591.4   183.8  5831.4   185.7  5871.4   185.4  5911.4   186.2  5991.4   185.4
  6062.5  185.58  6091.4   185.1  6191.4   187.6  6251.4   188.1  6331.4   188.1
  6351.4   187.5  6371.4   188.7  6411.4   188.3  6721.4   190.2  6820.6   189.9
#Mann= 5 ,-1 , 0
  3690.2     .06       0  4995.1     .07       0  5004.6     .05       0
  6062.5     .08       0  6721.4     .05       0
#XS Ineff= 2 , 0
                         5907.64          185.96
Permanent Ineff=
       F       F
Bank Sta=4995.1,5004.6
Exp/Cntr=0.3,0.1

Type RM Length L Ch R = 1 ,20751.8 ,1073.9,1146.7,1185.5
BEGIN DESCRIPTION:
Cross Section K161-00-00-X13
END DESCRIPTION:
XS GIS Cut Line= 3
      2961592.47     13912244.73      2959470.46     13911517.54
      2958050.86     13911768.42
#Sta/Elev= 30
  3179.3   191.9    4222   183.5  4299.3   183.8  4559.3   181.6  4699.3     182
  4739.3   181.6  4752.3  179.82  4986.2  180.19  4993.9   179.1  4998.3  176.99
  4998.8  175.44  5001.3  175.29  5001.7  176.95  5003.1  177.65  5032.8  179.62
  5205.5  179.24  5259.3   180.1  5279.3   179.2  5319.3   180.6  5582.4   179.8
    5719  180.68  5782.4     180  5822.4   180.6  6002.4   180.3  6242.4   181.2
  6382.4   182.6  6542.4   182.6  6582.4     184  6662.4   184.5    6864   184.7
#Mann= 5 ,-1 , 0
  3179.3     .06       0    4222     .08       0  4993.9     .07       0
  5003.1     .09       0    5719     .07       0
Bank Sta=4993.9,5003.1
Exp/Cntr=0.3,0.1

Type RM Length L Ch R = 1 ,19605.1 ,953.5,1027.2,1130.3
BEGIN DESCRIPTION:
Right Ineffective based on transition from downstream cross section
Cross Section K161-00-00-X12
END DESCRIPTION:
XS GIS Cut Line= 3
      2961362.55     13911508.44      2959194.38     13909692.82
      2956321.13     13909622.31
#Sta/Elev= 30
  3721.4  193.54  4411.4   179.6  4461.4  180.24 4826.74  176.62  4984.1   176.4
 4991.76  175.34 4995.45  172.45 5001.67  171.81 5012.81  176.05 5018.06   176.9
 5076.97  176.06 5207.07  176.83  5221.4  178.38  6201.4  176.67  6431.4  174.76
  6471.4  175.69  6491.4  174.76  6511.4  175.58  6759.4  176.08  7179.4  175.24
  7219.4  176.79  7259.4  175.33  7319.4  175.13  7449.4  177.13  7479.4  176.14
  7849.4  175.64  8139.4  176.51  8739.4  181.02  9209.4  188.74  9423.5  190.83
#Mann= 6 ,-1 , 0
  3721.4     .06       0  4411.4     .09       0 4991.76     .07       0
 5012.81     .09       0  5221.4     .08       0  7849.4     .05       0
#XS Ineff= 2 , 0
       0                    7175       0     180
Permanent Ineff=
       F       F
Bank Sta=4991.76,5012.81
Exp/Cntr=0.3,0.1

Type RM Length L Ch R = 1 ,18577.9 ,1009.7,1054.6,1060.6
BEGIN DESCRIPTION:
Right Ineffective based on transition from downstream cross section
Cross Section K161-00-00-X11
END DESCRIPTION:
XS GIS Cut Line= 3
      2961681.16     13911073.35      2960516.43     13908811.46
 2957678.9795448 13907297.168929
#Sta/Elev= 30
  3808.3   190.8  4027.8  187.21  4168.3   185.5  4468.3   178.9    4567  178.01
  4688.3   177.1  4767.1  174.39  4970.5  174.05  4988.2  172.91  4999.5  171.52
  5007.1  173.13  5020.1  175.04    5094  173.71  5223.5  174.29  5248.3   176.5
  5348.3     177  5708.3   177.3  5888.3   175.2  6288.3   176.3  6372.3  178.19
  6512.5   176.4  6772.5   175.4  7212.5   176.3  7792.5   174.6  8212.5   176.3
  8392.5   175.4  8632.5   176.9  8692.5   178.8  8765.5  179.07  9312.5   179.3
#Mann= 7 ,-1 , 0
  3808.3     .06       0  4027.8     .07       0    4567     .09       0
  4988.2    .065       0  5007.1     .09       0  6372.3     .07       0
  8765.5     .06       0
#XS Ineff= 2 , 0
       0                    7140       0     180
Permanent Ineff=
       F       F
Bank Sta=4988.2,5007.1
Exp/Cntr=0.3,0.1

Type RM Length L Ch R = 1 ,17523.3 ,1339.3,1200.5,826.5
BEGIN DESCRIPTION:
Right Ineffective based on transition from downstream cross section
Cross Section K161-00-00-X10
END DESCRIPTION:
XS GIS Cut Line= 3
      2962279.17     13910168.76      2961680.81     13908882.09
  2958878.097828  13906819.31654
#Sta/Elev= 30
  4117.3   177.5  4437.3   177.4  4757.3   175.6    4829  173.84  4937.2  173.95
    4993  172.08  4999.6  170.36  5006.4   172.1  5026.3   173.6  5151.2  175.37
    5195  174.71  5417.3     177  6076.3   175.5  6136.3   177.3  6256.3   176.7
  6316.3   177.8  6456.3   175.2  6596.3   177.7  6776.3   178.3  6996.3   177.3
  7116.3   175.3  7396.3   175.1  7696.3   177.4  8176.3   175.2  8276.3   176.4
  8416.3   175.4  8496.3   177.6  8776.3   179.1  8927.1  178.85  9016.3   177.8
#Mann= 5 ,-1 , 0
  4117.3     .08       0    4829     .09       0    4993    .065       0
  5006.4     .09       0  8927.1     .08       0
#XS Ineff= 2 , 0
       0                    7310       0
Permanent Ineff=
       F       F
Bank Sta=4993,5006.4
Exp/Cntr=0.3,0.1

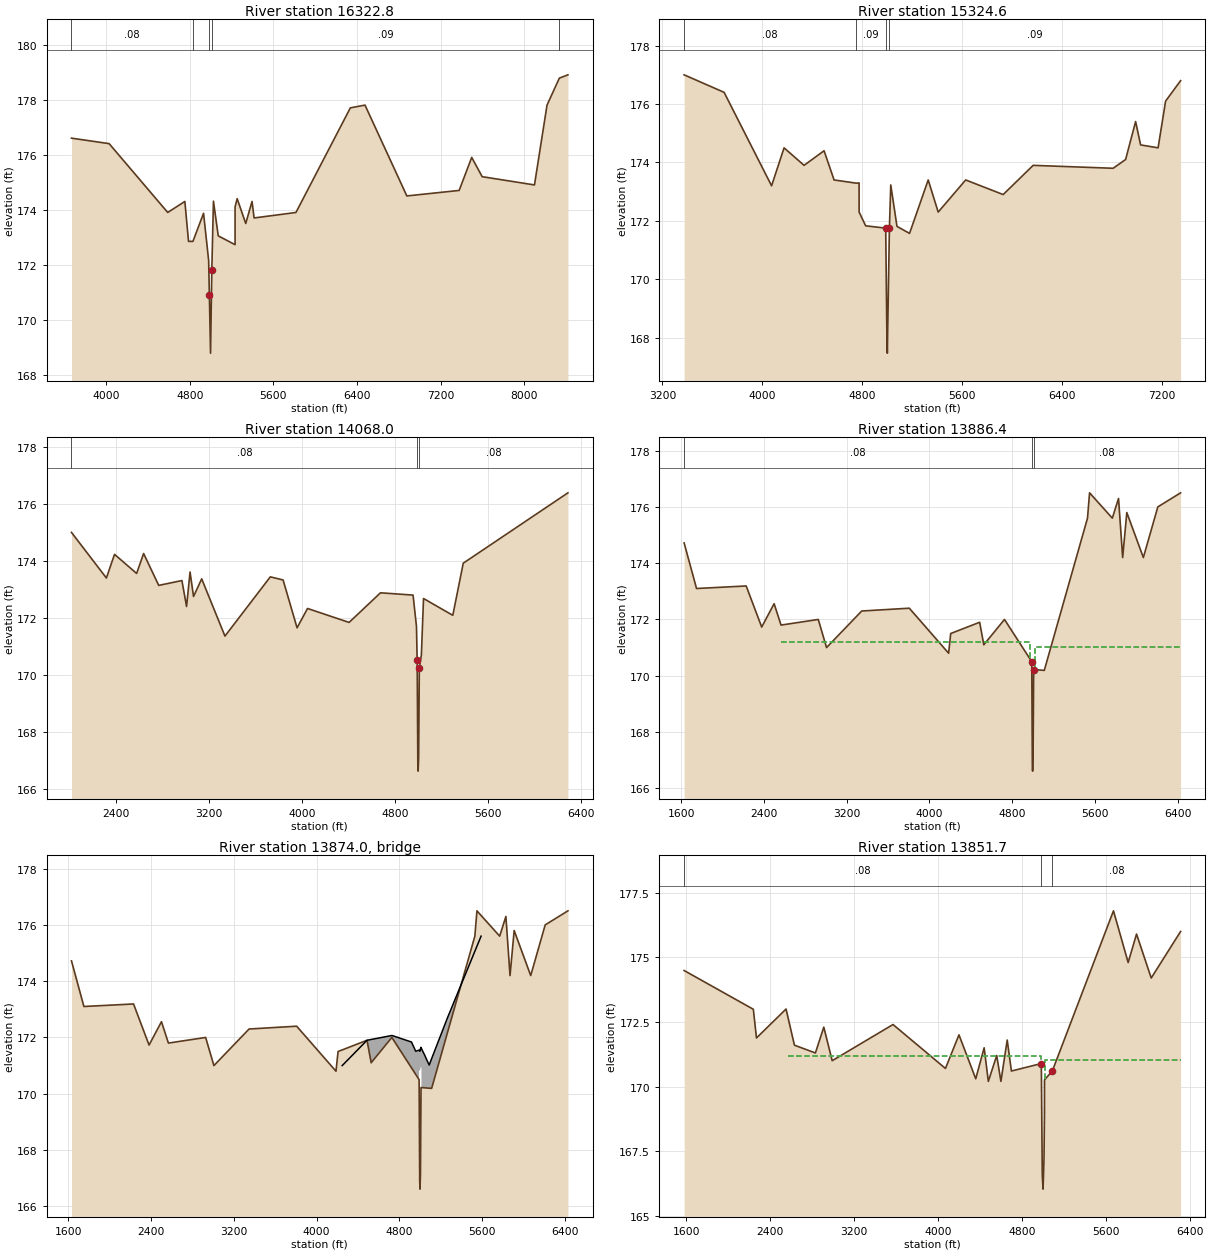
Type RM Length L Ch R = 1 ,16322.8 ,1023.7,998.2,966.4
BEGIN DESCRIPTION:
Right Ineffective based on transition from downstream cross section
Cross Section K161-00-00-X9
END DESCRIPTION:
XS GIS Cut Line= 4
      2963424.94     13909093.49      2962647.12      13908397.6
      2962057.92     13908273.35   2959423.25023  13906639.93261
#Sta/Elev= 30
  3669.9   176.6  4029.9   176.4  4589.9   173.9  4753.6   174.3  4788.7  172.85
  4830.8  172.85  4932.3  173.87    4981  172.16  4987.9  170.91  4999.2  168.79
  5011.3  171.81  5026.9  174.31  5072.9  173.05  5233.6  172.73  5233.6   174.1
  5253.6   174.4  5335.7   173.5  5395.7   174.3  5415.7   173.7  5815.7   173.9
  6335.7   177.7  6475.7   177.8  6875.7   174.5  7375.7   174.7  7495.7   175.9
  7595.7   175.2  8095.7   174.9  8215.7   177.8  8333.5  178.78  8415.7   178.9
#Mann= 5 ,-1 , 0
  3669.9     .08       0  4830.8     .09       0  4987.9    .065       0
  5011.3     .09       0  8333.5     .08       0
#XS Ineff= 2 , 0
       0                    7280       0
Permanent Ineff=
       F       F
Bank Sta=4987.9,5011.3
Exp/Cntr=0.3,0.1

Type RM Length L Ch R = 1 ,15324.6 ,1225,1256.6,1250
BEGIN DESCRIPTION:
Right Ineffective based on transition from downstream cross section
Cross Section K161-00-00-X8
END DESCRIPTION:
XS GIS Cut Line= 4
      2963908.88  13908146.79049      2962993.17     13907402.26
      2962242.19     13907341.42  2960398.178275  13906469.05038
#Sta/Elev= 30
  3373.2     177  3693.2   176.4  4073.2   173.2  4173.2   174.5  4333.2   173.9
  4493.2   174.4  4573.4   173.4  4751.1  173.29  4773.4   173.3 4773.95   172.3
 4826.15  171.83 4986.65  171.75 4995.65  168.21 4999.55  167.47 5016.25  171.75
 5027.05  173.23 5076.85  171.81 5177.35  171.57  5326.8   173.4  5406.8   172.3
  5626.8   173.4  5926.8   172.9  6166.8   173.9  6806.8   173.8  6906.8   174.1
  6986.8   175.4  7026.8   174.6  7166.8   174.5  7226.8   176.1  7346.8   176.8
#Mann= 4 ,-1 , 0
  3373.2     .08       0  4751.1     .09       0 4986.65    .065       0
 5016.25     .09       0
#XS Ineff= 2 , 0
       0                    7140       0
Permanent Ineff=
       F       F
Bank Sta=4986.65,5016.25
Exp/Cntr=0.3,0.1

Type RM Length L Ch R = 1 ,14068.0 ,190.2,181.6,165.1
BEGIN DESCRIPTION:
K161-00-00-S2_DIRT RD - U/S - XS4
Left ineffective at drainage area divide
END DESCRIPTION:
XS GIS Cut Line= 6
       2965219.5      13907472.2      2964538.23     13906811.16
      2963357.68     13906273.88       2962433.6     13906092.87
      2961359.25     13905982.15 2961359.150429713905982.1397385
#Sta/Elev= 30
  2019.2  174.99  2319.2  173.39  2389.2  174.22  2579.2  173.55  2639.2  174.25
  2769.2  173.13  2968.5   173.3  3008.5  172.39  3038.5   173.6  3068.5  172.74
  3138.5  173.36  3338.5  171.35  3728.5  173.43  3838.5  173.32  3958.5  171.64
  4048.5  172.32  4405.6  171.83  4675.6  172.87  4955.6  172.79    4985  171.69
  4990.9   170.5  4996.6   166.9  4999.2  166.61  5003.7   167.1  5009.5  170.22
  5027.1  170.69  5045.6  172.67  5297.2  172.08  5387.2  173.91  6287.2  176.38
#Mann= 3 ,-1 , 0
  2019.2     .08       0  4990.9    .065       0  5009.5     .08       0
Bank Sta=4990.9,5009.5
Exp/Cntr=0.5,0.3

Type RM Length L Ch R = 1 ,13886.4 ,35.2,34.7,34.4
BEGIN DESCRIPTION:
K161-00-00-S2_DIRT RD - U/S - XS3
Cross Section K161-00-00-S2_DIRT RD - U/S
END DESCRIPTION:
XS GIS Cut Line= 6
       2965425.9       13907353.      2965126.61      13906528.8
      2963570.87     13906075.93      2962797.15     13905977.28
       2962576.6     13905946.94      2961283.48     13905813.47
#Sta/Elev= 30
    1630  174.72    1750   173.1    2230  173.19    2380  171.73    2500  172.56
    2567   171.8    2927     172    3007     171    3347   172.3    3807   172.4
  4187.3   170.8  4207.3   171.5  4487.3   171.9  4527.3   171.1  4727.3     172
  4990.9   170.5  4996.6   166.9  4999.2  166.61  5003.7   167.1  5009.5  170.22
  5112.1  170.19  5529.9   175.6  5549.9   176.5  5769.9   175.6  5829.9   176.3
  5869.9   174.2  5909.9   175.8  6069.9   174.2  6209.9     176  6429.9   176.5
#Mann= 3 ,-1 , 0
    1630     .08       0  4990.9    .065       0  5009.5     .08       0
#XS Ineff= 3 ,-1
                            2570    4975   171.2  5023.5  6429.9  171.02
Permanent Ineff=
       F       F       F
Bank Sta=4990.9,5009.5
Exp/Cntr=0.5,0.3

Type RM Length L Ch R = 3 ,13874.0 ,,,
BEGIN DESCRIPTION:
DIRT ROAD 8880' US OF WARREN RANCH
Structure ID: K172-00-00-S2
END DESCRIPTION:
Bridge Culvert--1,0,-1,-1, 0
Deck Dist Width WeirC Skew NumUp NumDn MinLoCord MaxHiCord MaxSubmerge Is_Ogee
10,16,2.6,0, 35, 35, , , 0.95, 0, ,,,
  4247.3  4487.3  4727.9  4777.9  4787.9  4807.9  4817.9  4907.4  4915.6  4916.9
    4958  4989.7 4989.81  4989.9    4990  4990.9  4996.3  4996.6  4998.2  4999.2
  5002.1  5003.7  5007.6  5009.5 5013.29  5013.4  5013.5  5027.1  5039.8  5070.5
  5088.4  5112.1  5138.5  5265.3    5590
     171   171.9  172.07  172.01     172  171.97  171.96  171.85  171.84  171.84
  171.51  171.55  171.55  171.55  171.55  171.54  171.52  171.52  171.51  171.52
  171.57  171.59  171.65  171.64  171.61  171.61  171.61   171.5  171.41  171.16
  171.02  171.25   171.5   172.7   175.6
                                                                                
                          170.85  170.85  170.84  170.82  170.82  170.81  170.82
  170.87  170.89  170.95  170.94  170.91
                                        
  4247.3  4487.3  4727.9  4777.9  4787.9  4807.9  4817.9  4907.4  4915.6  4916.9
    4958  4989.7 4989.81  4989.9    4990  4990.9  4996.3  4996.6  4998.2  4999.2
  5002.1  5003.7  5007.6  5009.5 5013.29  5013.4  5013.5  5027.1  5039.8  5070.5
  5088.4  5112.1  5138.5  5265.3    5590
     171   171.9  172.07  172.01     172  171.97  171.96  171.85  171.84  171.84
  171.51  171.55  171.55  171.55  171.55  171.54  171.52  171.52  171.51  171.52
  171.57  171.59  171.65  171.64  171.61  171.61  171.61   171.5  171.41  171.16
  171.02  171.25   171.5   172.7   175.6
                                                                                
                          170.85  170.85  170.84  170.82  170.82  170.81  170.82
  170.87  170.89  170.95  170.94  170.91
                                        
BR Coef= 1 , 1 , 0 ,1.25, 0 ,,,0.8,-1,2,0,
WSPro=,,,, 1 ,,,, 0 ,,,, 0 ,,,,-1 ,-1 ,-1 , 0 , 0 , 0 , 0 , 0
BC Design=,, 0 ,, 0 ,,,,,,
BC HTab HWMax=177.21

Type RM Length L Ch R = 1 ,13851.7 ,13.6,12.7,10.4
BEGIN DESCRIPTION:
K161-00-00-S2_DIRT RD - D/S - XS2
Cross Section K161-00-00-S2_DIRT RD - D/S
END DESCRIPTION:
XS GIS Cut Line= 6
      2965471.22       13907334.      2965155.24     13906472.32
      2965102.97     13906461.98      2963591.39     13906041.73
      2962586.19     13905914.13      2961413.46     13905783.61
#Sta/Elev= 30
  1577.5  174.49  2237.5  172.99  2267.5  171.88  2549.4     173  2629.4   171.6
  2829.4   171.3  2909.4   172.3  2989.4     171  3569.4   172.4  4069.4   170.7
  4198.3     172  4358.3   170.3  4438.3   171.5  4478.3   170.2  4558.3   171.2
  4598.3   170.2  4658.3   171.8  4698.3   170.6  4983.7  170.89  4992.7  166.57
  5000.2  166.03  5009.1   167.2  5013.5  168.89 5014.09  170.26  5088.4   170.6
  5671.6   176.8  5811.6   174.8  5891.6   175.9  6031.6   174.2  6311.6     176
#Mann= 3 ,-1 , 0
  1577.5     .08       0  4983.7    .065       0  5088.4     .08       0
#XS Ineff= 3 ,-1
                            2570 4978.33   171.2 5020.17  6311.6  171.02
Permanent Ineff=
       F       F       F
Bank Sta=4983.7,5088.4
Exp/Cntr=0.5,0.3