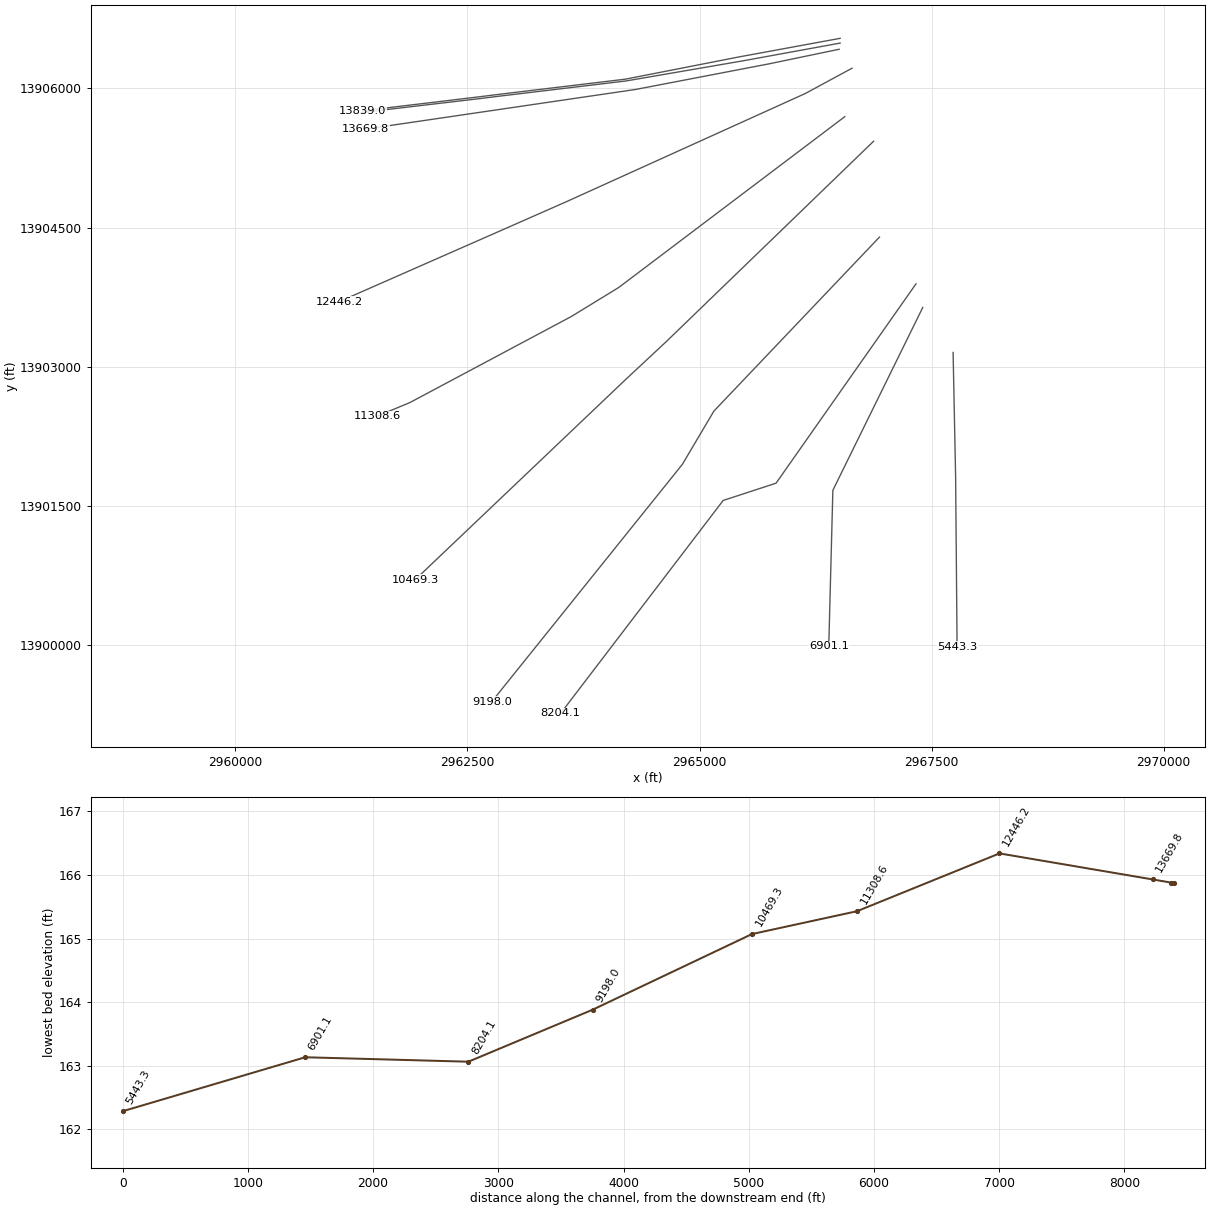
HEC-RAS study K172-00-00.prj: K172-00-00

--- K172-00-00.g01 (geometry) --- (continued)

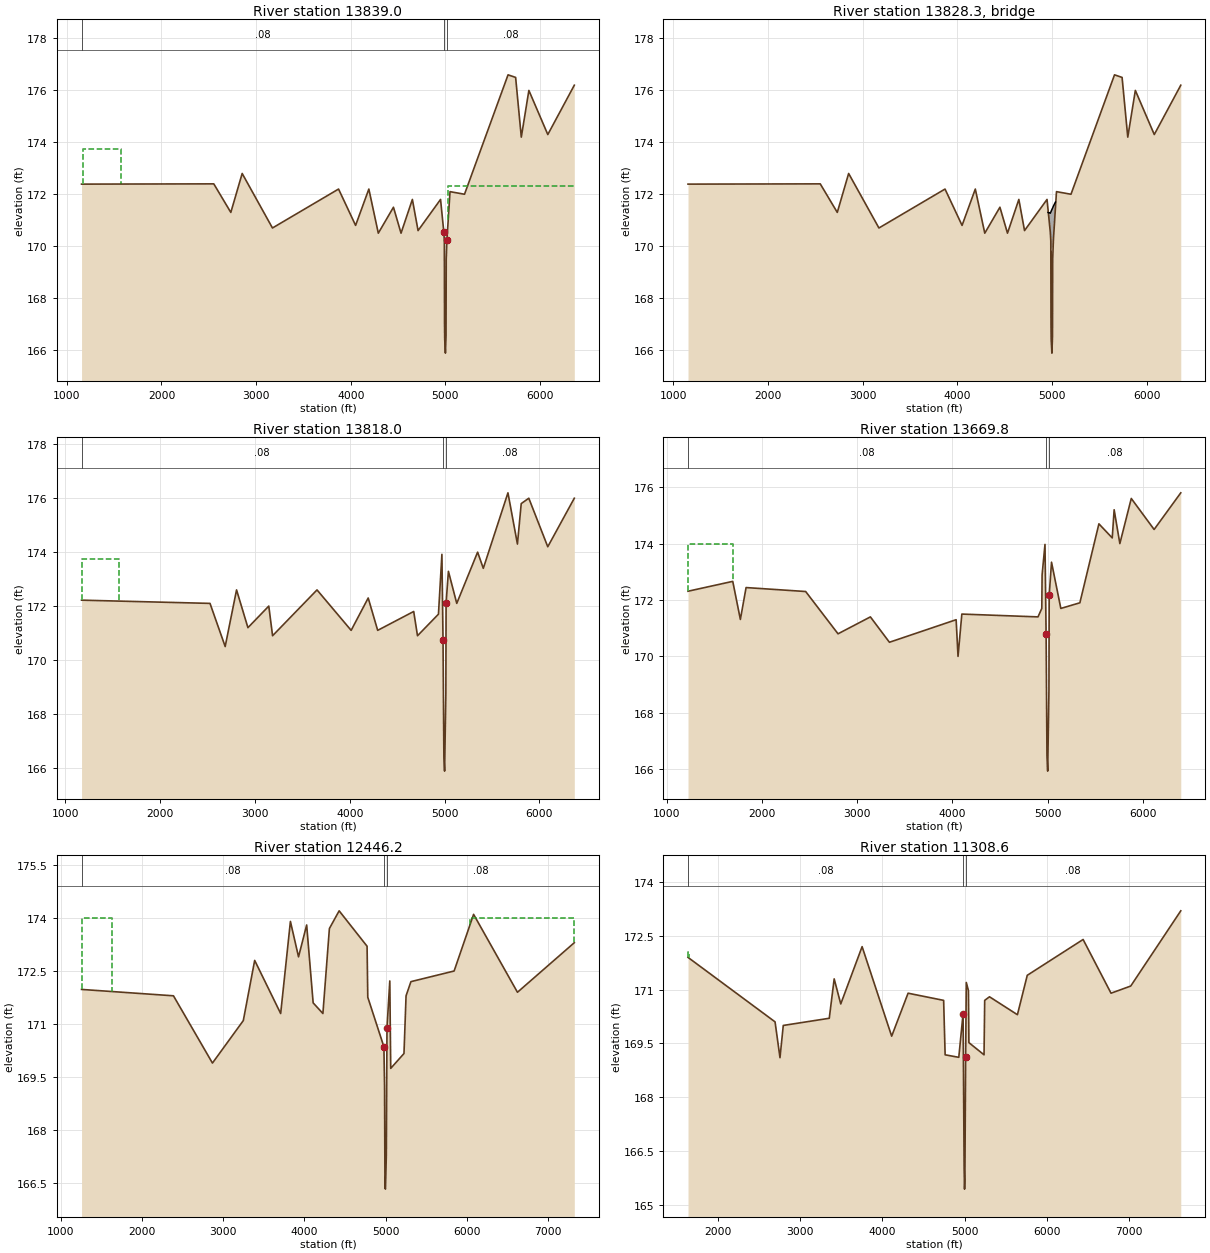
Type RM Length L Ch R = 1 ,13839.0 ,20.6,21,20
BEGIN DESCRIPTION:
K161-00-00-S2A_PIPELINE - U/S - XS3
Cross Section K161-00-00-S2A_PIPELINE - U/S
END DESCRIPTION:
XS GIS Cut Line= 6
      2966514.76     13906538.95      2965435.72     13906340.73
      2964200.82     13906099.02      2962793.38     13905930.05
       2962641.4     13905910.85       2961370.4     13905758.63
#Sta/Elev= 30
  1155.8  172.39  2552.9   172.4  2732.9   171.3  2852.9   172.8  3172.9   170.7
  3871.2   172.2  4051.2   170.8  4191.2   172.2  4291.2   170.5  4451.2   171.5
  4531.2   170.5  4651.2   171.8  4711.2   170.6  4948.8   171.8  4983.7  170.53
  4988.8   170.2  4990.9  167.01  4992.7  166.42  5000.2  165.88  5006.6  166.52
  5008.8   169.5  5016.2  170.24  5048.8   172.1    5202     172    5662   176.6
    5742   176.5    5802   174.2    5882     176    6082   174.3    6362   176.2
#Mann= 3 ,-1 , 0
  1155.8     .08       0  4983.7    .065       0  5016.2     .08       0
#XS Ineff= 3 ,-1
  1170.5  1570.5  173.74    2295  4961.9   170.6  5029.7    6362   172.3
Permanent Ineff=
       F       F       F
Bank Sta=4983.7,5016.2
Exp/Cntr=0.5,0.3

Type RM Length L Ch R = 3 ,13828.3 ,,,
BEGIN DESCRIPTION:
PL1_K172-00-00-S2A
END DESCRIPTION:
Bridge Culvert--1,0,-1,-1, 0
Deck Dist Width WeirC Skew NumUp NumDn MinLoCord MaxHiCord MaxSubmerge Is_Ogee
10,2,2.6,0, 13, 13, , , 0.95, 0, ,,,
    4960  4983.7 4985.51  4985.6  4990.9    4992  4992.7  5000.2  5006.6  5009.1
  5013.5 5014.42    5038
   171.3  171.27  171.29  171.29  171.33  171.34  171.35  171.41  171.46  171.48
  171.52  171.53   171.7
                   169.8  169.79  169.83  169.84  169.85  169.91  169.96  169.98
  170.02  170.03
    4960  4983.7 4985.51  4985.6  4990.9    4992  4992.7  5000.2  5006.6  5009.1
  5013.5 5014.42    5038
   171.3  171.27  171.29  171.29  171.33  171.34  171.35  171.41  171.46  171.48
  171.52  171.53   171.7
                   169.8  169.79  169.83  169.84  169.85  169.91  169.96  169.98
  170.02  170.03
Pier Skew, UpSta & Num, DnSta & Num=  ,4992.7, 2 ,4992.7, 2 , 0 , 0 , 0 ,,
      .6      .6
   165.4  170.85
      .6      .6
   165.4  170.85
BR Coef= 1 , 1 , 1 ,1.25, 0 ,,,0.8,-1,2,0,
WSPro=,,,, 1 ,,,, 0 ,,,, 0 ,,,,-1 ,-1 ,-1 , 0 , 0 , 0 , 0 , 0
BC Design=,, 0 ,, 0 ,,,,,,
BC HTab HWMax=176.67

Type RM Length L Ch R = 1 ,13818.0 ,143.2,148.2,152.2
BEGIN DESCRIPTION:
K161-00-00-S2A_PIPELINE - D/S - XS2
Cross Section K161-00-00-S2A_PIPELINE - D/S
END DESCRIPTION:
XS GIS Cut Line= 6
      2966514.76      13906487.8      2965476.82     13906298.13
      2964206.84      13906079.6      2962795.82      13905910.2
      2962643.91     13905891.01      2961372.74     13905741.39
#Sta/Elev= 30
  1170.5  172.22  2525.6   172.1  2685.6   170.5  2805.6   172.6  2925.6   171.2
  3145.6     172  3185.6   170.9  3654.4   172.6  4014.4   171.1  4194.4   172.3
  4294.4   171.1  4674.4   171.8  4714.4   170.9  4935.5   171.7  4971.9  173.92
  4983.7  170.74  4992.7  166.42  5000.2  165.88  5013.5  168.74  5016.2  172.12
  5040.5  173.29  5128.6   172.1  5348.6     174  5408.6   173.4  5668.6   176.2
  5768.6   174.3  5808.6   175.8  5888.6     176  6088.6   174.2  6368.6     176
#Mann= 3 ,-1 , 0
  1170.5     .08       0  4983.7    .065       0  5016.2     .08       0
#XS Ineff= 3 ,-1
  1170.5  1570.5  173.74 2318.18 4965.23   170.6 5026.37  6368.6   172.3
Permanent Ineff=
       F       F       F
Bank Sta=4983.7,5016.2
Exp/Cntr=0.5,0.3

Type RM Length L Ch R = 1 ,13669.8 ,1166.3,1223.6,1275.3
BEGIN DESCRIPTION:
K161-00-00-S2A_PIPELINE - D/S - XS1
Left Ineffective at Limits of Drainage Divide
END DESCRIPTION:
XS GIS Cut Line= 4
       2966504.5      13906421.3      2965744.87      13906263.3
      2964310.34     13905988.08      2961401.52     13905560.92
#Sta/Elev= 30
  1221.8  172.31  1691.8  172.66  1771.8  171.31  1831.8  172.44  2457.7   172.3
  2797.7   170.8  3137.7   171.4  3337.7   170.5  4038.4   171.3  4058.4     170
  4098.4   171.5  4898.4   171.4  4938.4   171.7  4941.6  172.89  4971.9  173.97
  4983.7  170.79  4992.7  166.47  5000.2  165.93  5013.5  168.79  5016.2  172.17
  5040.5  173.34  5138.4   171.7  5338.4   171.9  5538.4   174.7  5678.4   174.2
  5698.4   175.2  5758.4     174  5878.4   175.6  6118.4   174.5  6398.4   175.8
#Mann= 3 ,-1 , 0
  1221.8     .08       0  4983.7    .065       0  5016.2     .08       0
#XS Ineff= 2 , 0
       0  1691.8     174               0
Permanent Ineff=
       F       F
Bank Sta=4983.7,5016.2
Exp/Cntr=0.3,0.1

Type RM Length L Ch R = 1 ,12446.2 ,1114.6,1137.6,1172.1
BEGIN DESCRIPTION:
Left Ineffective at Limits of Drainage Divide
Right Ineffective based on transition from upstream cross section and floodplain limits
Right Limits of Cross Section based on Limits of Drainage Divide
Cross Section K161-00-00-X7
END DESCRIPTION:
XS GIS Cut Line= 5
      2966642.59     13906216.81      2966139.81     13905944.76
      2963567.39     13904779.85      2962952.83     13904508.96
      2961122.02     13903703.89
#Sta/Elev= 30
  1256.8  171.98  2388.5   171.8  2868.5   169.9  3248.5   171.1  3388.5   172.8
  3708.5   171.3  3828.5   173.9  3928.5   172.9  4028.5   173.8  4108.5   171.6
  4228.5   171.3  4308.5   173.7  4428.5   174.2  4772.4   173.2    4781  171.76
  4979.6  170.36  4987.7  169.23  4992.7  166.37  4998.7  166.34  5009.4  167.29
  5017.6  170.89  5052.2  172.22  5063.5  169.75  5226.8  170.17  5252.4   171.8
  5312.4   172.2    5844   172.5    6084   174.1    6624   171.9    7324   173.3
#Mann= 3 ,-1 , 0
  1256.8     .08       0  4979.6    .065       0  5017.6     .08       0
#XS Ineff= 2 , 0
       0 1626.75     174    6040       0     174
Permanent Ineff=
       F       F
Bank Sta=4979.6,5017.6
Exp/Cntr=0.3,0.1

Type RM Length L Ch R = 1 ,11308.6 ,823.7,839.3,890.6
BEGIN DESCRIPTION:
Left Ineffective at Limits of Drainage Divide
Right Ineffective based on transition from upstream cross section and floodplain limits
Right Limits of Cross Section based on Limits of Drainage Divide
Cross Section K161-00-00-X6
END DESCRIPTION:
XS GIS Cut Line= 5
      2966564.81  13905695.14266      2964129.07      13903854.6
      2963618.66      13903542.1      2961880.76     13902615.71
  2961529.955933  13902469.65917
#Sta/Elev= 30
    1632   171.9    2692   170.1    2752   169.1    2792     170    3352   170.2
    3412   171.3    3492   170.6    3752   172.2    4112   169.7    4312   170.9
  4744.9   170.7  4763.1  169.18  4929.4  169.11  4981.8  170.33  4994.6     166
  4999.6  165.43  5003.6   165.7  5012.9  169.12  5020.9   171.2  5047.1  170.97
  5052.5  169.52  5236.9  169.18  5244.9   170.7  5303.4   170.8  5643.4   170.3
  5763.4   171.4  6443.4   172.4  6783.4   170.9  7023.4   171.1  7632.8   173.2
#Mann= 3 ,-1 , 0
    1632     .08       0  4981.8     .07       0  5012.9     .08       0
#XS Ineff= 2 , 0
       0 1648.67  172.04    6065       0
Permanent Ineff=
       F       F
Bank Sta=4981.8,5012.9
Exp/Cntr=0.3,0.1

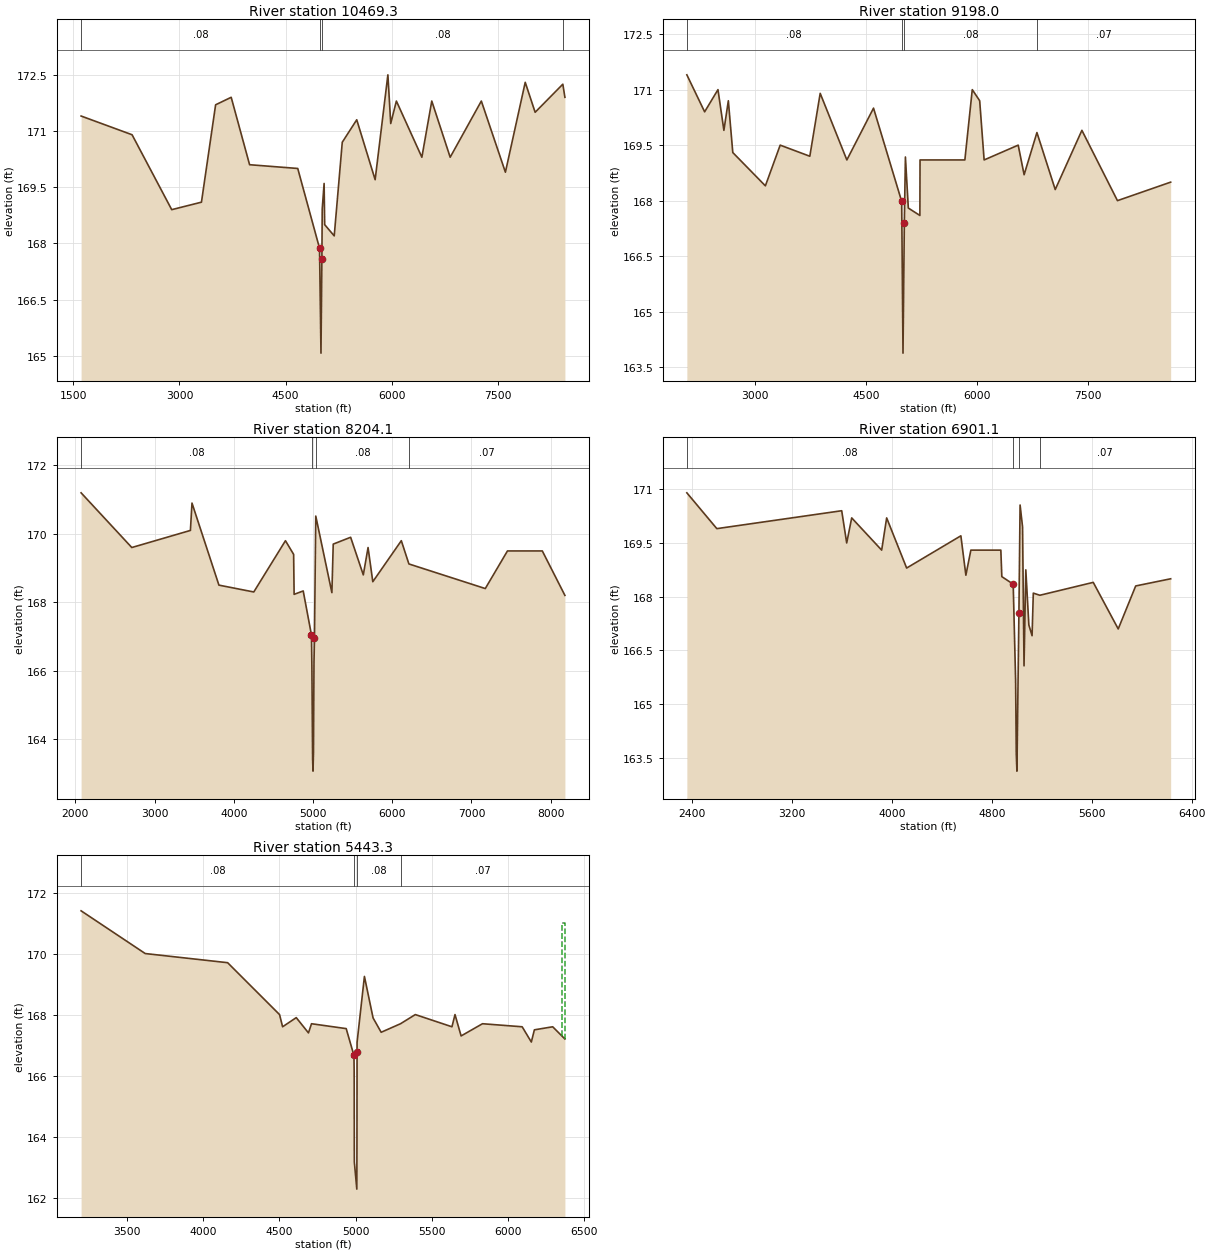
Type RM Length L Ch R = 1 ,10469.3 ,1191.5,1271.3,1137.3
BEGIN DESCRIPTION:
Right Ineffective based on transition from upstream cross section and floodplain limits
Right Limits of Cross Section based on Limits of Drainage Divide
Cross Section K161-00-00-X5
END DESCRIPTION:
XS GIS Cut Line= 4
      2966875.57  13905430.78822      2964640.07     13903270.31
      2964198.15     13902857.98      2961937.22     13900707.17
#Sta/Elev= 30
  1611.1   171.4  2331.1   170.9  2891.1   168.9  3311.1   169.1  3511.1   171.7
  3731.1   171.9  3991.1   170.1  4671.1     170    4979  167.87  4999.3  165.07
  5012.3  167.59    5017  168.92  5043.7   169.6  5051.6   168.5  5186.5   168.2
  5300.1   170.7  5504.5   171.3  5764.5   169.7  5944.5   172.5  5984.5   171.2
  6064.5   171.8  6424.5   170.3  6564.5   171.8  6824.5   170.3  7264.5   171.8
  7604.5   169.9  7884.5   172.3  8024.5   171.5  8415.5  172.25    8445   171.9
#Mann= 4 ,-1 , 0
  1611.1     .08       0    4979     .07       0  5012.3     .08       0
  8415.5     .07       0
#XS Ineff= 2 , 0
       0                    6180       0
Permanent Ineff=
       F       F
Bank Sta=4979,5012.3
Exp/Cntr=0.3,0.1

Type RM Length L Ch R = 1 ,9198.0  ,1159.3,993.9,855
BEGIN DESCRIPTION:
Right Ineffective based on transition from upstream cross section and floodplain limits
Right Limits of Cross Section based on Limits of Drainage Divide
Cross Section K161-00-00-X4
END DESCRIPTION:
XS GIS Cut Line= 4
       2966938.5  13904397.78442      2965154.51     13902523.01
      2964815.74      13901950.6      2962762.97     13899394.44
#Sta/Elev= 30
  2081.7   171.4  2321.7   170.4  2501.7     171  2581.7   169.9  2641.7   170.7
  2701.7   169.3  3141.7   168.4  3341.7   169.5  3741.7   169.2  3881.7   170.9
  4241.7   169.1  4601.7   170.5 4981.65  167.98 4999.65  163.88 5017.65   167.4
 5032.15  169.18 5071.45   167.8 5227.55   167.6  5229.6   169.1  5834.8   169.1
  5934.8     171  6034.8   170.7  6094.8   169.1  6554.8   169.5  6634.8   168.7
  6807.7  169.84  7054.8   168.3  7414.8   169.9  7894.8     168  8613.2   168.5
#Mann= 4 ,-1 , 0
  2081.7     .08       0 4981.65     .07       0 5017.65     .08       0
  6807.7     .07       0
#XS Ineff= 2 , 0
       0                    8040       0
Permanent Ineff=
       F       F
Bank Sta=4981.65,5017.65
Exp/Cntr=0.3,0.1

Type RM Length L Ch R = 1 ,8204.1  ,1017.4,1303,1428.8
BEGIN DESCRIPTION:
Right Ineffective based on transition from upstream cross section and floodplain limits
Right Limits of Cross Section based on Limits of Drainage Divide
Cross Section K161-00-00-X3
END DESCRIPTION:
XS GIS Cut Line= 4
  2967331.818145  13903894.00998       2965824.7     13901747.18
      2965254.75     13901560.87      2963504.03      13899267.4
#Sta/Elev= 30
  2072.1   171.2  2712.1   169.6  3452.1   170.1  3472.1   170.9  3812.1   168.5
  4252.1   168.3  4652.1   169.8  4755.2   169.4 4761.35  168.23 4876.25  168.33
 4980.55  167.04 4985.65  166.14 4994.95  163.41 5000.15  163.06 5005.85  163.61
 5012.45  166.26 5018.25  166.94 5034.75  170.52 5238.25  168.28  5255.2   169.7
  5474.9   169.9  5634.9   168.8  5694.9   169.6  5754.9   168.6  6114.9   169.8
  6210.3  169.12  7174.9   168.4  7454.9   169.5  7894.9   169.5  8180.2   168.2
#Mann= 4 ,-1 , 0
  2072.1     .08       0 4985.65     .07       0 5034.75     .08       0
  6210.3     .07       0
#XS Ineff= 2 , 0
       0                    7660       0
Permanent Ineff=
       F       F
Bank Sta=4980.55,5018.25
Exp/Cntr=0.3,0.1

Type RM Length L Ch R = 1 ,6901.1  ,1395.2,1457.8,1402.6
BEGIN DESCRIPTION:
Right Ineffective at Limits of Drainage Divide
Cross Section K161-00-00-X2B
END DESCRIPTION:
XS GIS Cut Line= 3
  2967404.750302  13903639.59713      2966436.51     13901670.55
 2966392.318256313899991.1265705
#Sta/Elev= 30
  2357.6   170.9  2597.6   169.9  3597.6   170.4  3637.6   169.5  3677.6   170.2
  3917.6   169.3  3957.6   170.2  4117.6   168.8  4551.9   169.7  4591.9   168.6
  4631.9   169.3  4871.9   169.3  4879.8  168.56  4970.9  168.35  4990.2  165.67
  4995.5  163.62  5000.7  163.13  5016.7  167.55    5026  170.56  5045.8  169.95
  5057.6  166.07  5071.9  168.75  5096.3  167.21  5122.1  166.91  5131.9   168.1
  5184.4  168.04  5611.9   168.4  5811.9   167.1  5951.9   168.3  6231.9   168.5
#Mann= 4 ,-1 , 0
  2357.6     .08       0  4970.9     .07       0  5016.7     .08       0
  5184.4     .07       0
#XS Ineff= 2 , 0
       0                    6192       0
Permanent Ineff=
       F       F
Bank Sta=4970.9,5016.7
Exp/Cntr=0.3,0.1

Type RM Length L Ch R = 1 ,5443.3  ,122.5,102.8,101.1
BEGIN DESCRIPTION:
K161-00-00-S01_WARREN RANCH RD - U/S - XS4
Right Ineffective at Limits of Drainage Divide
END DESCRIPTION:
XS GIS Cut Line= 3
  2967731.721749  13903155.05506      2967758.98     13901805.89
 2967774.5237967 13899985.954243
#Sta/Elev= 30
  3202.4   171.4  3622.4     170  4162.4   169.7  4502.4     168  4522.4   167.6
  4611.8   167.9  4691.8   167.4  4711.8   167.7    4939  167.54  4989.8  166.66
  4991.3  166.11  4992.3  163.17  5008.6  162.28  5009.6  163.91  5010.2  166.76
  5010.3  167.09  5058.4  169.25  5115.1  167.89  5168.1  167.42    5295   167.7
  5391.8     168  5631.8   167.6  5651.8     168  5691.8   167.3  5831.8   167.7
  6091.8   167.6  6151.8   167.1  6171.8   167.5  6291.8   167.6  6371.8   167.2
#Mann= 4 ,-1 , 0
  3202.4     .08       0  4989.8     .07       0  5010.2     .08       0
    5295     .07       0
#XS Ineff= 2 , 0
       0                    6350       0     171
Permanent Ineff=
       F       F
Bank Sta=4989.8,5010.2
Exp/Cntr=0.5,0.3