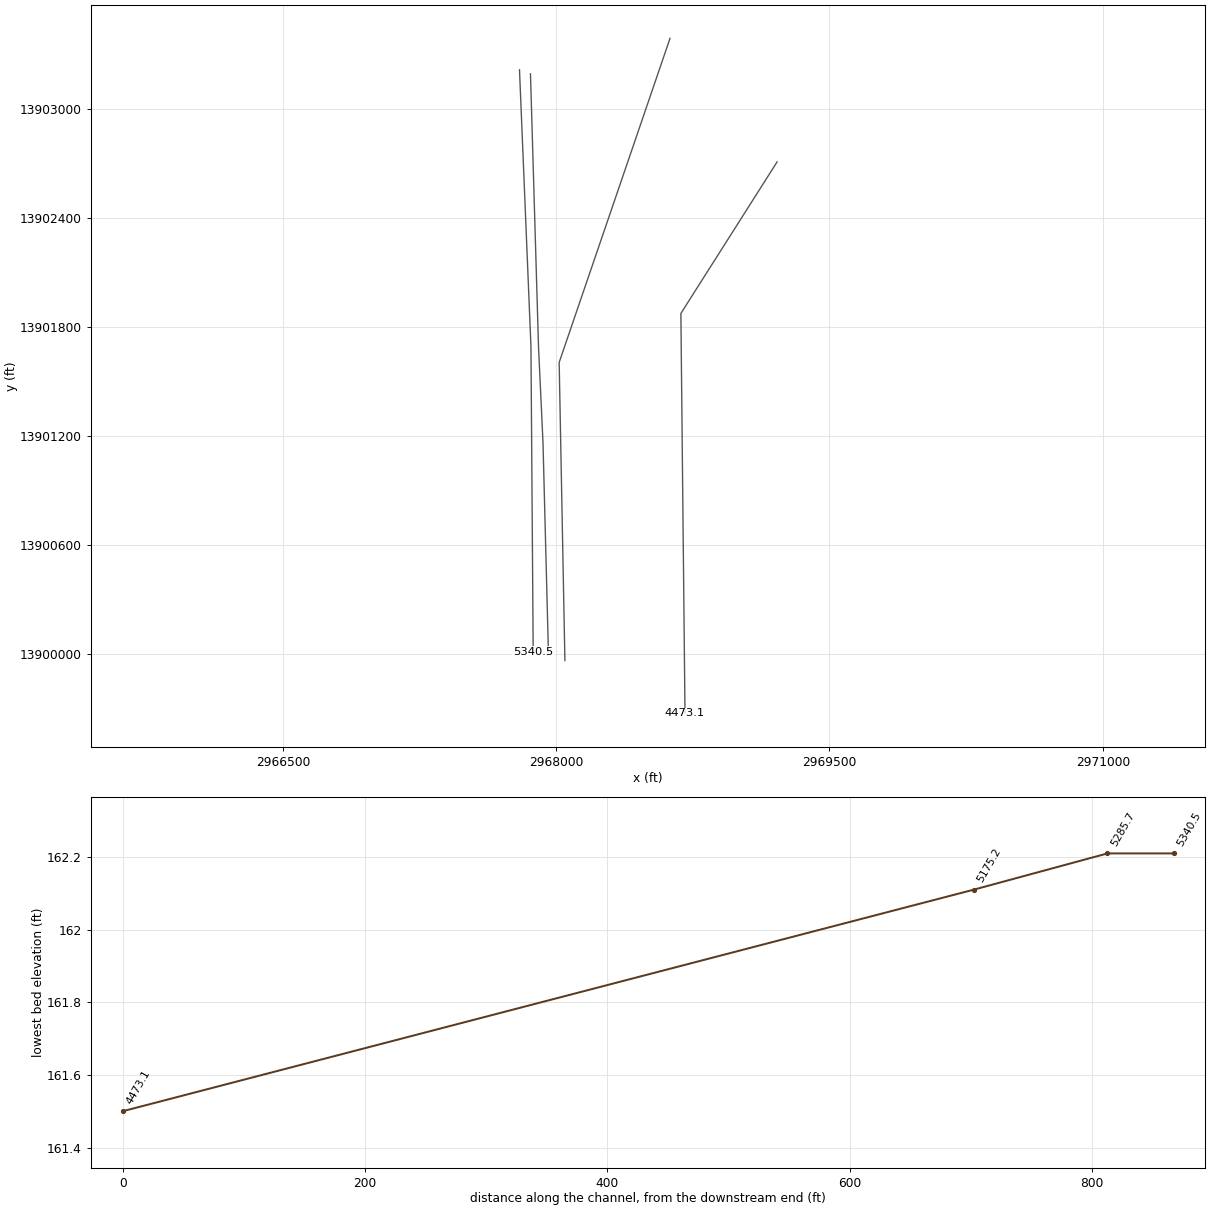
HEC-RAS study K172-00-00.prj: K172-00-00

--- K172-00-00.g01 (geometry) --- (continued)

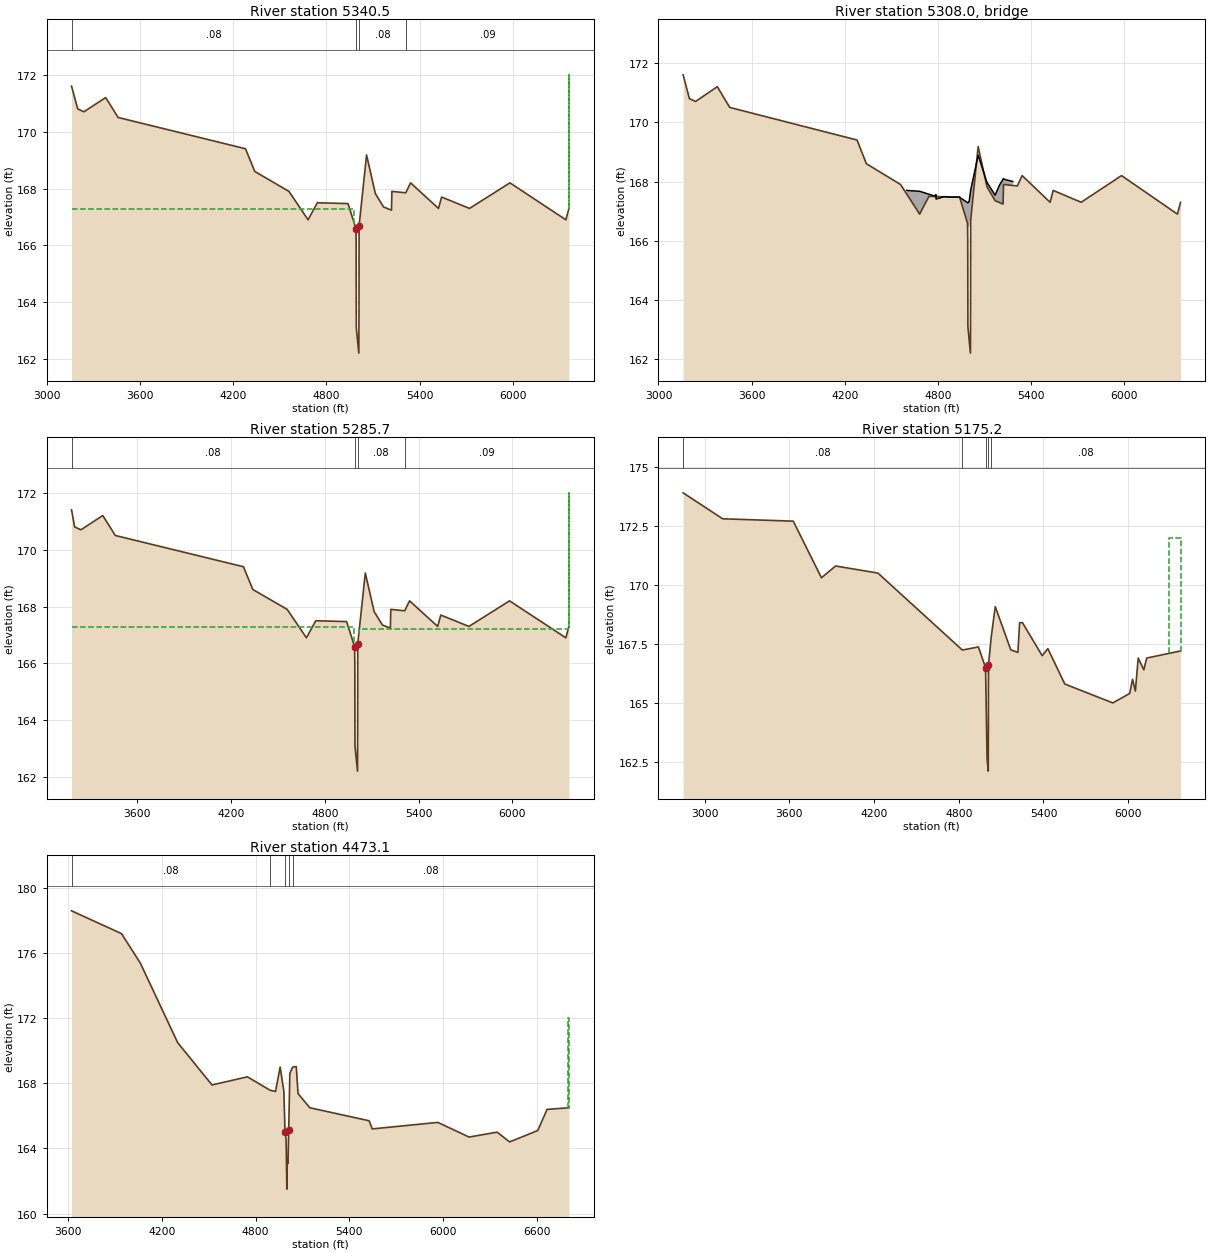
Type RM Length L Ch R = 1 ,5340.5  ,43,54.8,68.5
BEGIN DESCRIPTION:
K161-00-00-S01_WARREN RANCH RD - U/S - XS3
Right Ineffective at Limits of Drainage Divide
Cross Section K161-00-00-S01_WARREN RANCH RD - U/S
END DESCRIPTION:
XS GIS Cut Line= 4
  2967798.454616  13903215.49661      2967861.32     13901693.82
 2967871.422890613900313.8366638 2967873.6191389 13900013.844703
#Sta/Elev= 30
  3158.6   171.6  3198.6   170.8  3238.6   170.7  3378.6   171.2  3458.6   170.5
  4278.6   169.4  4338.6   168.6  4558.6   167.9  4681.6   166.9  4741.6   167.5
    4939  167.47  4989.8  166.59  4991.3  166.04  4992.3   163.1  5008.6  162.21
  5009.6  163.84  5010.2  166.69  5058.4  169.18  5115.1  167.82  5168.1  167.35
  5218.8  167.24  5221.6   167.9  5310.8  167.85  5341.6   168.2  5521.6   167.3
  5541.6   167.7  5721.6   167.3  5981.6   168.2  6341.6   166.9  6361.6   167.3
#Mann= 4 ,-1 , 0
  3158.6     .08       0  4989.8     .07       0  5010.2     .08       0
  5310.8     .09       0
#XS Ineff= 3 ,-1
  3158.6  4979.8  167.29  5020.3    6360   167.2    6360    6361     172
Permanent Ineff=
       F       F       F
Bank Sta=4989.8,5010.2
Exp/Cntr=0.5,0.3

Type RM Length L Ch R = 3 ,5308.0  ,,,
BEGIN DESCRIPTION:
WARREN RANCH ROAD
Structure ID: K172-00-00-S01
END DESCRIPTION:
Bridge Culvert--1,0,-1,-1, 0
Deck Dist Width WeirC Skew NumUp NumDn MinLoCord MaxHiCord MaxSubmerge Is_Ogee
10,16,2.6,0, 42, 42, , , 0.95, 0, ,,,
  4598.6  4682.1    4778  4786.7  4787.6  4840.5  4840.7  4891.8  4892.4    4939
  4940.2  4989.8  4991.2 4991.31  4991.4 4991.51  4991.6  4991.7  5000.1  5000.3
  5000.5  5000.6    5001  5008.5 5008.61  5009.2 5009.29  5009.4  5009.5  5010.2
  5010.3  5058.4  5114.9  5115.1  5167.4  5168.1    5198  5218.3  5218.8  5221.5
  5222.1  5281.6
   167.7  167.67  167.51  167.56  167.41  167.49  167.49  167.47  167.47  167.48
  167.46  167.29  167.28  167.28  167.28  167.28  167.28  167.28  167.32  167.32
  167.32  167.32  167.34  167.65  167.66  167.68  167.69  167.69  167.69  167.71
  167.71  168.89  167.97  167.97  167.54  167.55   167.9  168.07  168.08   168.1
  168.08     168
                                                                                
                                                  166.44  166.44  166.48  166.48
  166.48  166.48   166.5  166.81  166.82  166.84  166.85
                                                                                
                
  4598.6  4682.1    4778  4786.7  4787.6  4840.5  4840.7  4891.8  4892.4    4939
  4940.2  4989.8  4991.2 4991.31  4991.4 4991.51  4991.6  4991.7  5000.1  5000.3
  5000.5  5000.6    5001  5008.5 5008.61  5009.2 5009.29  5009.4  5009.5  5010.2
  5010.3  5058.4  5114.9  5115.1  5167.4  5168.1    5198  5218.3  5218.8  5221.5
  5222.1  5281.6
   167.7  167.67  167.51  167.56  167.41  167.49  167.49  167.47  167.47  167.48
  167.46  167.29  167.28  167.28  167.28  167.28  167.28  167.28  167.32  167.32
  167.32  167.32  167.34  167.65  167.66  167.68  167.69  167.69  167.69  167.71
  167.71  168.89  167.97  167.97  167.54  167.55   167.9  168.07  168.08   168.1
  168.08     168
                                                                                
                                                  166.44  166.44  166.48  166.48
  166.48  166.48   166.5  166.81  166.82  166.84  166.85
                                                                                
                
BR Coef= 1 , 1 , 0 ,1.25, 0 ,,,0.8,0,2,0,
WSPro=,,,, 1 ,,,, 0 ,,,, 0 ,,,,-1 ,-1 ,-1 , 0 , 0 , 0 , 0 , 0
BC Design=,, 0 ,, 0 ,,,,,,
BC HTab HWMax=176.81

Type RM Length L Ch R = 1 ,5285.7  ,134.7,110.5,96.9
BEGIN DESCRIPTION:
K161-00-00-S01_WARREN RANCH RD - D/S - XS2
Right Ineffective at Limits of Drainage Divide
Cross Section K161-00-00-S01_WARREN RANCH RD - D/S
END DESCRIPTION:
XS GIS Cut Line= 5
  2967858.728969  13903193.20545      2967902.91     13901691.03
      2967927.44     13901166.48 2967950.612614513900266.7559461
 2967957.178025113900011.8404789
#Sta/Elev= 30
  3178.6   171.4  3198.6   170.8  3238.6   170.7  3378.6   171.2  3458.6   170.5
  4278.6   169.4  4338.6   168.6  4558.6   167.9  4681.6   166.9  4741.6   167.5
    4939  167.47  4989.8  166.59  4991.3  166.04  4992.3   163.1  5008.6  162.21
  5009.6  163.84  5010.2  166.69  5058.4  169.18  5115.1  167.82  5168.1  167.35
  5218.8  167.24  5221.6   167.9  5310.8  167.85  5341.6   168.2  5521.6   167.3
  5541.6   167.7  5721.6   167.3  5981.6   168.2  6341.6   166.9  6361.6   167.3
#Mann= 4 ,-1 , 0
  3178.6     .08       0  4989.8     .07       0  5010.2     .08       0
  5310.8     .09       0
#XS Ineff= 3 ,-1
  3178.6 4983.13  167.29 5016.97    6360   167.2    6360    6361     172
Permanent Ineff=
       F       F       F
Bank Sta=4989.8,5010.2
Exp/Cntr=0.5,0.3

Type RM Length L Ch R = 1 ,5175.2  ,664.9,702.1,681.9
BEGIN DESCRIPTION:
K161-00-00-S01_WARREN RANCH RD - D/S - XS1
Right Ineffective at Limits of Drainage Divide
Cross Section S1-DS
END DESCRIPTION:
XS GIS Cut Line= 3
      2968624.71     13903388.55       2968016.2     13901605.83
 2968047.704147313899966.1651895
#Sta/Elev= 30
  2847.2   173.9  3127.2   172.8  3627.2   172.7  3827.2   170.3  3927.2   170.8
  4227.2   170.5  4825.1  167.24    4939  167.37  4989.8  166.49  5000.1  162.67
  5008.6  162.11  5009.6  163.74  5010.2  166.59  5029.3  167.77  5058.4  169.08
  5168.1  167.25  5218.8  167.14  5230.9   168.4  5250.9   168.4  5390.9     167
  5430.9   167.3  5550.9   165.8  5890.9     165  6010.9   165.4  6030.9     166
  6050.9   165.5  6070.9   166.9  6110.9   166.4  6130.9   166.9  6370.9   167.2
#Mann= 5 ,-1 , 0
  2847.2     .08       0  4825.1     .12       0  4989.8     .07       0
  5010.2     .12       0  5029.3     .08       0
#XS Ineff= 2 , 0
       0                    6291       0     172
Permanent Ineff=
       F       F
Bank Sta=4989.8,5010.2
Exp/Cntr=0.3,0.1

Type RM Length L Ch R = 1 ,4473.1  ,3609,3696.9,3726.6
BEGIN DESCRIPTION:
Right Ineffective at Limits of Drainage Divide
Cross Section K161-00-00-X2A
END DESCRIPTION:
XS GIS Cut Line= 3
      2969212.41     13902708.77      2968684.29     13901875.35
  2968706.91094313899675.4485505
#Sta/Elev= 30
  3620.7   178.6  3940.7   177.2  4060.7   175.4  4300.7   170.5  4520.7   167.9
  4747.4   168.4  4892.1  167.58  4927.4   167.5  4957.2     169  4981.1  167.51
  4988.3  165.02  4995.4  164.53  5000.1   161.5  5002.9  163.28  5007.3  163.08
    5012  165.14  5019.3  168.61  5037.3     169  5060.5  169.03  5071.8  167.37
  5147.4   166.5  5527.4   165.7  5547.4   165.2  5967.4   165.6  6167.4   164.7
  6347.4     165  6427.4   164.4  6607.4   165.1  6667.4   166.4  6807.4   166.5
#Mann= 5 ,-1 , 0
  3620.7     .08       0  4892.1     .12       0  4988.3     .07       0
    5012     .12       0  5037.3     .08       0
#XS Ineff= 2 , 0
       0                    6800       0     172
Permanent Ineff=
       F       F
Bank Sta=4988.3,5012
Exp/Cntr=0.3,0.1

Chan Stop Cuts=-1
Use User Specified Reach Order=0
User Specified Reach Order=K172-00-00      ,K172-00-00_0045